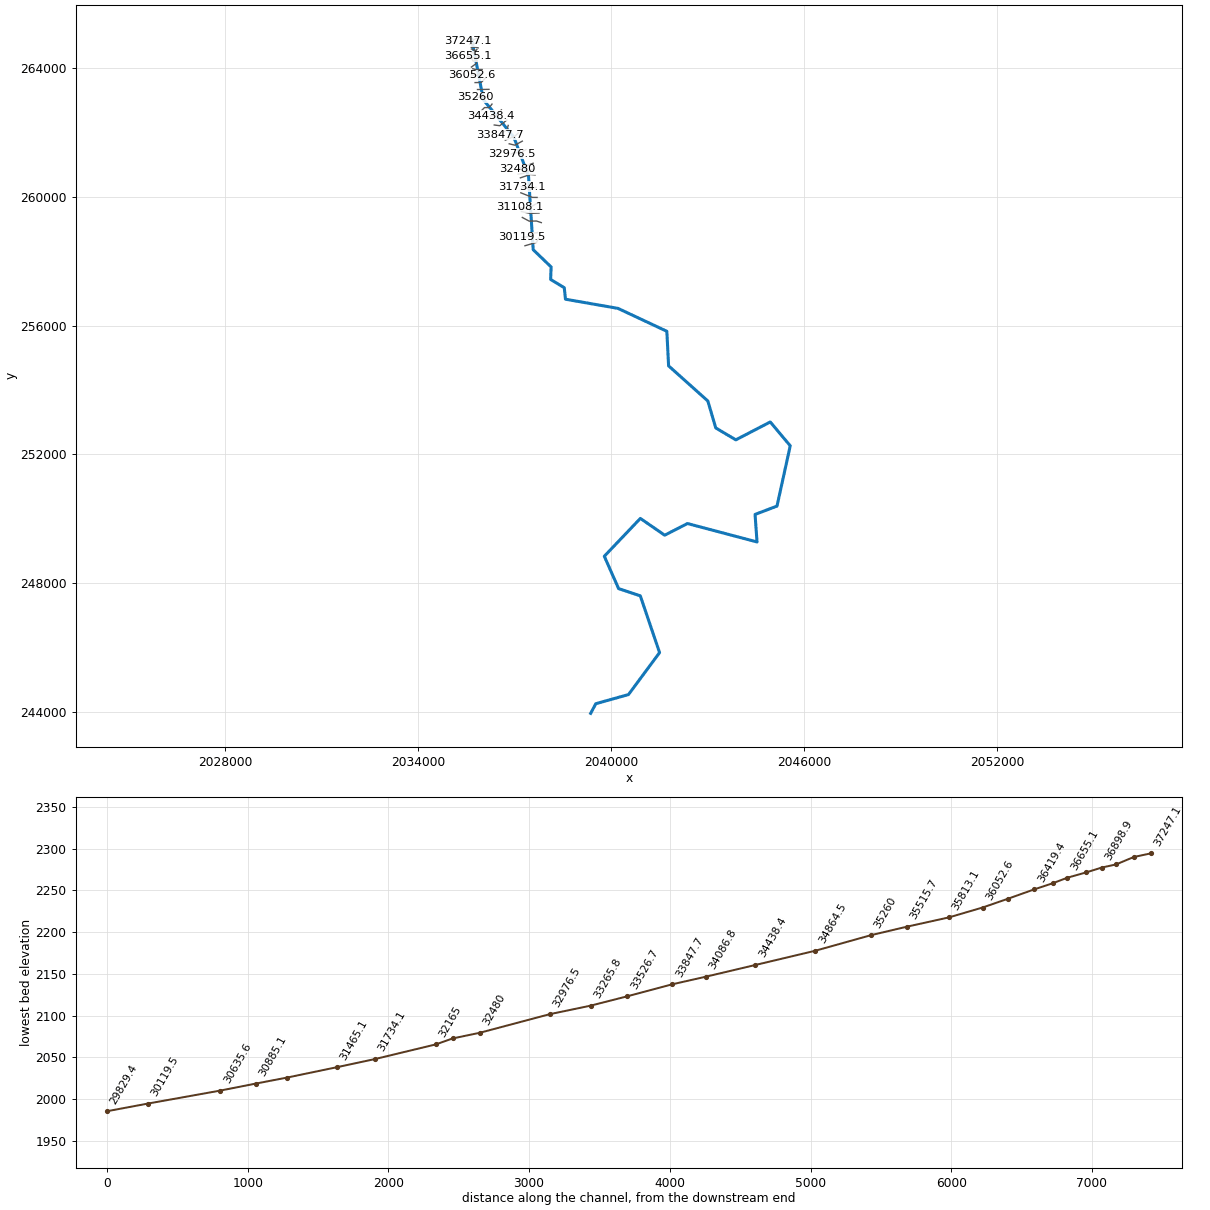
--- HNGRDCK.prj (project) ---

Proj Title=HNGRDCK
Current Plan=p01
Geom File=g01
Flow File=f01
Plan File=p01
DSS Export Rating Curves=0
DSS Export Rating Curve Sorted=0
DSS Export Volume Flow Curves=0
DXF OffsetX=0
DXF OffsetY=0
DXF ScaleX=0
DXF ScaleY=0

--- HNGRDCK.p01 (plan) ---

Plan Title=Floodplain
Program Version=4.00
Geom File=g01
Flow File=f01
K Sum by GR=0
Std Step Tol=0.01
Critical Tol=0.01
Num of Std Step Trials=20
Max Error Tol=0.3
Flow Tol Ratio=0.001
Split Flow NTrial=30
Split Flow Tol=0.02
Split Flow Ratio=0.02
Log Output Level=0
Friction Slope Method=1
Unsteady Friction Slope Method=2
Unsteady Bridges Friction Slope Method=1
Global Log Level=0
CheckData=False
Run HTab=0
Run UNet=0
Run PostProcess=0
UNET Theta=0
UNET Theta Warmup=0
UNET ZTol=0
UNET ZSATol=0
UNET MxIter=0
UNET MaxInSteps=0
UNET DtIC=0
UNET DtMin=0
UNET MaxCRTS=0
UNET WFStab=0
UNET SFStab=0
UNET WFX=0
UNET SFX=0
UNET DSS MLevel=0
UNET DZMax Abort=0
UNET Convert EG Bridges=0
UNET Use Existing IB Tables=0
UNET Froude Limit=0
UNET Froude Power=0
Write IC File=0
Echo Input=False
Echo Output=False
Write Detailed=0

--- HNGRDCK.f01 (steady flow) ---

Flow Title=NFF Regression Equation
Program Version=4.00
Number of Profiles=1
Profile Names=P100yr
River Rch & RM=HNGRDCK,Main      ,37247.1
432.4463
River Rch & RM=HNGRDCK,Main      ,36898.9
588.4293
River Rch & RM=HNGRDCK,Main      ,34864.5
633.9017
River Rch & RM=HNGRDCK,Main      ,34086.8
684.3888
River Rch & RM=HNGRDCK,Main      ,32976.5
754.8233
River Rch & RM=HNGRDCK,Main      ,29829.4
837.8838
River Rch & RM=HNGRDCK,Main      ,26934.3
923.7476
River Rch & RM=HNGRDCK,Main      ,23262.7
988.9003
River Rch & RM=HNGRDCK,Main      ,17776.9
1092.316
River Rch & RM=HNGRDCK,Main      ,16945.2
2016.334
River Rch & RM=HNGRDCK,Main      ,11365.4
2117.452
River Rch & RM=HNGRDCK,Main      ,395.1
2341.296
River Rch & RM=HNGRDCK,Main      ,276.9
2341.652
Boundary for River Rch & Prof#=HNGRDCK,Main      ,1
Up Type=0
Dn Type=3
Dn Slope=0.000935

--- HNGRDCK.g01 (geometry) ---

Geom Title=USGS 10m DEM
Program Version=4.00

River Reach=HNGRDCK     ,Main
Reach XY= 30
     2035667.276      264901.994     2036026.902      263026.993
     2036977.666      261854.818     2037431.286      260644.569
     2037576.451      258361.241     2038133.743      257824.783
     2038118.284      257435.629     2038542.597      257178.949
     2038580.071      256821.571     2040212.509      256536.732
     2041732.227      255824.108     2041787.212      254748.483
     2043007.170      253656.823     2043253.750      252819.015
     2043877.396      252448.056     2044948.360      253003.612
     2045570.105      252263.594     2045157.859      250388.101
     2044475.815      250128.868     2044536.697      249272.988
     2042373.521      249845.742     2041665.717      249482.922
     2040908.983      250004.853     2039787.876      248828.256
     2040232.323      247822.249     2040907.257      247597.376
     2041506.563      245832.098     2040539.829      244527.174
     2039522.535      244242.515     2039363.683      243942.189

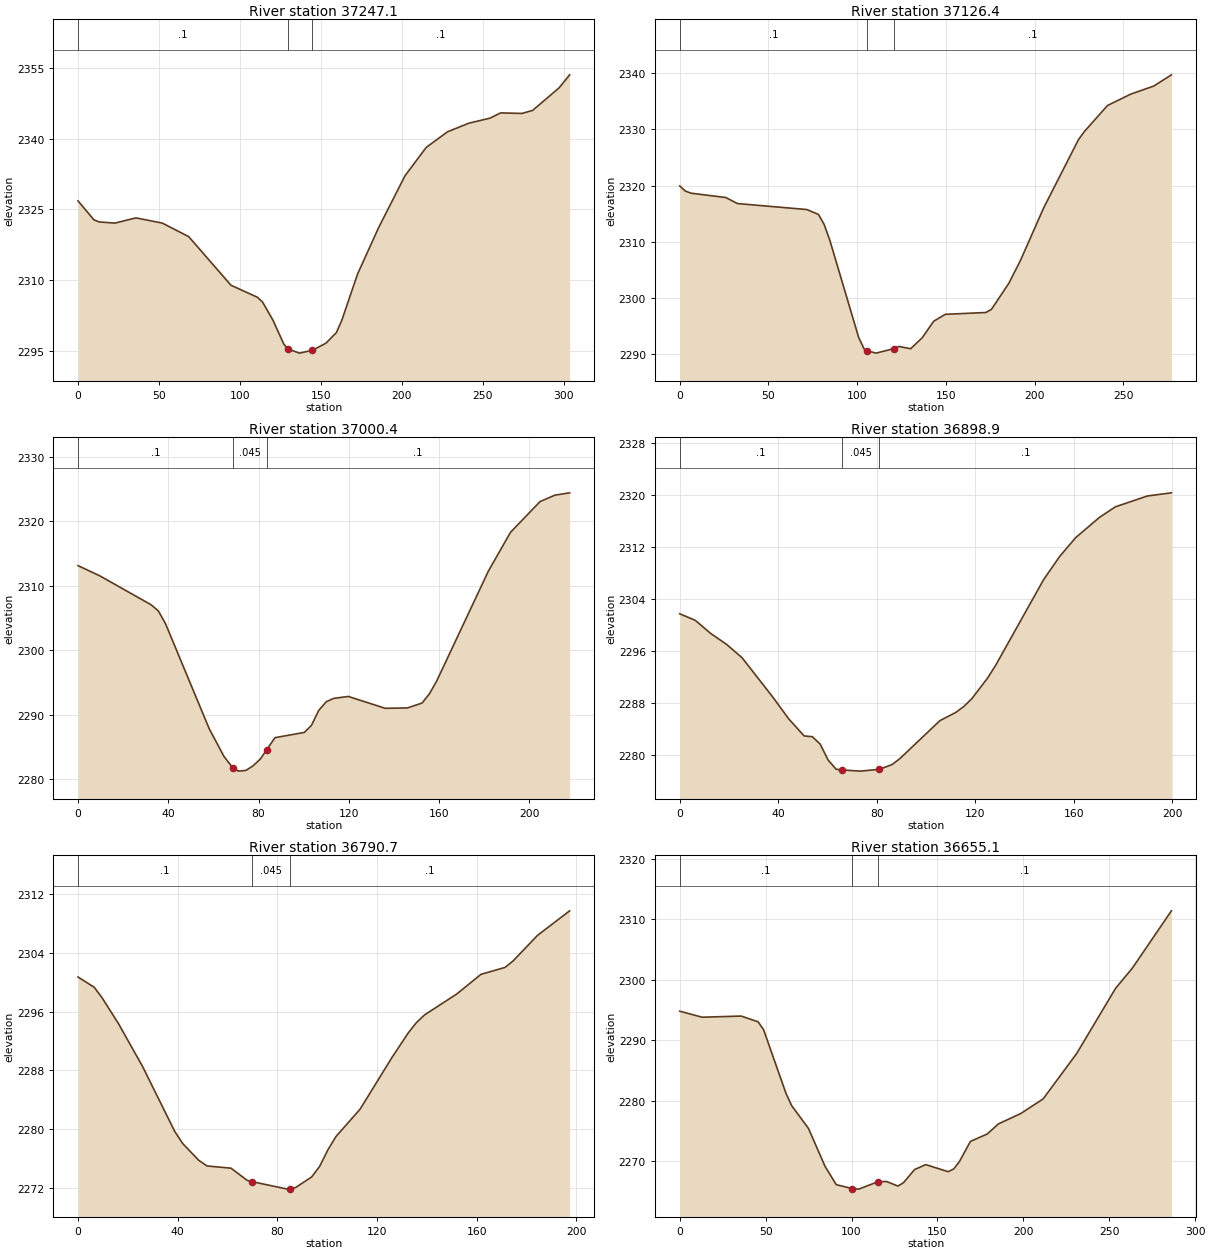
Type RM Length L Ch R = 1 ,37247.1,122.4,120.7,119.1
XS GIS Cut Line= 3
     2035816.017      264934.155     2035636.330      264849.259
     2035531.642      264841.447
#Sta/Elev= 30
       0 2326.83     9.8 2322.81    13.0 2322.35    22.8 2322.10    35.8 2323.21
    52.1 2322.10    68.4 2319.22    94.5 2308.89   110.8 2306.34   114.0 2305.32
   120.5 2301.42   127.1 2296.40   129.8 2295.33   136.8 2294.46   144.8 2295.06
   153.1 2296.56   159.6 2298.82   162.9 2301.38   172.7 2311.27   185.7 2321.14
   202.0 2332.16   215.1 2338.19   228.3 2341.52   241.4 2343.33   254.5 2344.41
   261.1 2345.53   274.2 2345.41   280.8 2346.05   297.2 2350.86   303.7 2353.62
#Mann= 3 , 0 , 0
       0     0.1       0   129.8   0.045       0   144.8     0.1       0
Bank Sta=129.8,144.8
Exp/Cntr=0.3,0.1

Type RM Length L Ch R = 1 ,37126.4,139.3,126,111.4
XS GIS Cut Line= 3
     2035867.059      264816.968     2035696.747      264752.384
     2035601.955      264753.947
#Sta/Elev= 30
       0 2319.93     3.2 2319.00     6.5 2318.63    26.0 2317.86    32.5 2316.79
    71.6 2315.72    78.1 2314.86    81.3 2313.11    84.6 2310.20   100.8 2292.92
   104.1 2290.73   105.5 2290.55   110.6 2290.12   120.5 2290.91   123.6 2291.31
   130.1 2290.90   136.6 2292.86   143.1 2295.81   149.6 2297.04   172.4 2297.36
   175.6 2297.92   185.4 2302.56   192.0 2306.67   205.0 2315.99   224.6 2328.16
   227.9 2329.60   241.0 2334.27   254.1 2336.30   267.1 2337.74   277.0 2339.74
#Mann= 3 , 0 , 0
       0     0.1       0   105.5   0.045       0   120.5     0.1       0
Bank Sta=105.5,120.5
Exp/Cntr=0.3,0.1

Type RM Length L Ch R = 1 ,37000.4,101.8,101.5,98.7
XS GIS Cut Line= 3
     2035864.976      264637.280     2035761.330      264662.801
     2035650.392      264656.030
#Sta/Elev= 30
       0 2313.09     9.7 2311.50    32.4 2307.02    35.6 2306.07    38.8 2304.08
    58.2 2287.76    64.7 2283.50    68.6 2281.73    71.2 2281.22    74.4 2281.33
    77.6 2282.04    80.9 2283.13    83.6 2284.52    87.3 2286.41   100.3 2287.22
   103.5 2288.33   106.7 2290.64   110.0 2291.97   113.3 2292.50   119.8 2292.80
   136.2 2290.96   146.0 2291.02   152.5 2291.78   155.8 2293.24   159.0 2295.21
   181.9 2312.25   191.7 2318.26   204.8 2323.03   211.4 2324.02   217.9 2324.38
#Mann= 3 , 0 , 0
       0     0.1       0    68.6   0.045       0    83.6     0.1       0
Bank Sta=68.6,83.6
Exp/Cntr=0.3,0.1

Type RM Length L Ch R = 1 ,36898.9,112.2,108.2,106
XS GIS Cut Line= 3
     2035823.309      264587.801     2035792.580      264547.697
     2035654.559      264603.947
#Sta/Elev= 30
       0 2301.71     6.3 2300.70    12.6 2298.67    19.0 2297.00    25.3 2294.94
    37.9 2288.82    44.2 2285.54    50.5 2282.89    53.8 2282.78    57.0 2281.64
    60.2 2279.20    63.5 2277.76      66 2277.65    73.2 2277.47      81 2277.74
    86.2 2278.48    89.4 2279.41   105.6 2285.24   112.1 2286.52   115.3 2287.42
   118.6 2288.64   125.0 2291.82   128.3 2293.80   147.7 2306.95   154.2 2310.52
   160.7 2313.42   170.4 2316.56   176.9 2318.19   189.8 2319.85   199.6 2320.34
#Mann= 3 , 0 , 0
       0     0.1       0      66   0.045       0      81     0.1       0
Bank Sta=66,81
Exp/Cntr=0.3,0.1

Type RM Length L Ch R = 1 ,36790.7,120.1,135.6,150.7
XS GIS Cut Line= 2
     2035806.642      264423.738     2035629.559      264510.718
#Sta/Elev= 30
       0 2300.73     6.5 2299.33     9.7 2297.88    16.2 2294.39    25.9 2288.53
    38.8 2279.67    42.0 2278.01    48.5 2275.70    51.8 2274.94    61.4 2274.64
    67.9 2272.98      70 2272.79    84.1 2271.78      85 2271.84    87.3 2271.99
    93.8 2273.45    97.0 2274.90   100.3 2277.15   103.5 2278.95   113.2 2282.69
   126.1 2289.80   132.6 2293.13   135.8 2294.50   139.1 2295.56   152.0 2298.41
   161.7 2301.09   171.4 2302.04   174.6 2302.92   184.4 2306.41   197.3 2309.76
#Mann= 3 , 0 , 0
       0     0.1       0      70   0.045       0      85     0.1       0
Bank Sta=70,85
Exp/Cntr=0.3,0.1

Type RM Length L Ch R = 1 ,36655.1,106,105.2,104.3
XS GIS Cut Line= 3
     2035826.434      264354.468     2035667.580      264319.051
     2035556.642      264373.218
#Sta/Elev= 30
       0 2294.80    13.0 2293.80    35.8 2293.99    45.6 2293.04    48.8 2291.74
    61.8 2281.23    65.1 2279.18    74.9 2275.40    84.6 2269.10    91.1 2266.07
   100.3 2265.43   104.2 2265.33   115.3 2266.55   120.4 2266.59   127.0 2265.84
   130.2 2266.38   136.7 2268.57   143.2 2269.39   156.2 2268.22   159.5 2268.67
   162.8 2269.89   169.2 2273.23   179.0 2274.46   185.5 2276.13   198.5 2277.85
   211.5 2280.26   231.0 2287.76   253.7 2298.58   263.5 2301.94   286.2 2311.42
#Mann= 3 , 0 , 0
       0     0.1       0   100.3   0.045       0   115.3     0.1       0
Bank Sta=100.3,115.3
Exp/Cntr=0.3,0.1

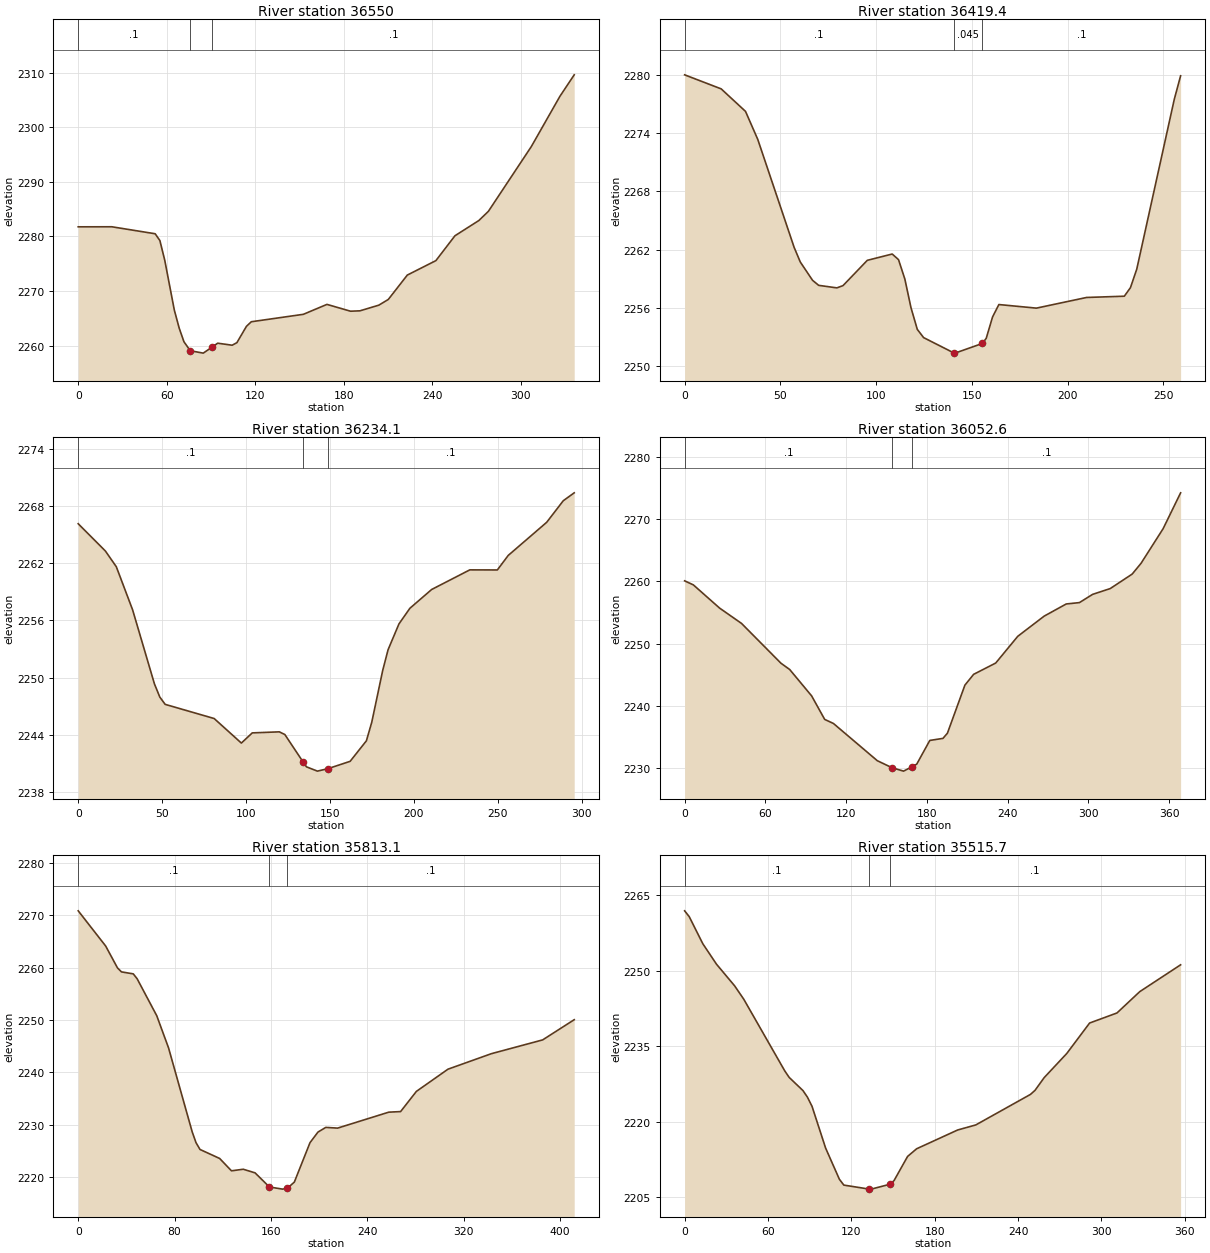
Type RM Length L Ch R = 1 ,36550,120.1,130.6,141.4
XS GIS Cut Line= 4
     2035828.778      264244.138     2035710.028      264222.784
     2035660.549      264305.075     2035552.736      264357.159
#Sta/Elev= 30
       0 2281.76    22.8 2281.77    52.2 2280.49    55.4 2279.24    58.7 2275.63
    65.2 2266.49    68.5 2263.19    71.7 2260.71      76 2259.06    84.8 2258.62
      91 2259.76    94.6 2260.44   104.4 2260.07   107.6 2260.53   114.1 2263.53
   117.4 2264.37   152.7 2265.73   168.7 2267.55   184.7 2266.30   191.1 2266.37
   203.9 2267.41   210.3 2268.45   223.2 2272.92   242.6 2275.57   255.5 2280.12
   271.7 2282.91   278.2 2284.60   307.3 2296.46   326.7 2305.67   336.4 2309.61
#Mann= 3 , 0 , 0
       0     0.1       0      76   0.045       0      91     0.1       0
Bank Sta=76,91
Exp/Cntr=0.3,0.1

Type RM Length L Ch R = 1 ,36419.4,199.3,185.4,170.3
XS GIS Cut Line= 3
     2035831.903      264223.304     2035784.507      264136.846
     2035655.861      264041.013
#Sta/Elev= 30
       0 2280.02    19.1 2278.57    31.8 2276.25    38.2 2273.36    57.2 2262.22
    60.4 2260.72    66.8 2258.83    70.0 2258.31    79.5 2258.05    82.7 2258.28
    95.4 2260.89   108.4 2261.54   111.7 2260.96   115.0 2258.96   118.2 2256.01
   121.5 2253.77   124.8 2252.92   140.5 2251.35   141.2 2251.32   155.5 2252.32
   157.5 2252.85   160.8 2255.05   164.1 2256.33   183.7 2255.96   209.9 2257.06
   229.6 2257.19   232.8 2258.07   236.1 2259.98   255.7 2277.50   259.0 2279.92
#Mann= 3 , 0 , 0
       0     0.1       0   140.5   0.045       0   155.5     0.1       0
Bank Sta=140.5,155.5
Exp/Cntr=0.3,0.1

Type RM Length L Ch R = 1 ,36234.1,172.1,181.4,190.5
XS GIS Cut Line= 3
     2035990.236      263963.409     2035766.799      263969.138
     2035698.049      263990.492
#Sta/Elev= 30
       0 2266.17    16.2 2263.30    22.7 2261.65    32.4 2257.12    45.4 2249.34
    48.6 2247.95    51.8 2247.18    81.0 2245.69    97.2 2243.11   103.7 2244.18
   119.8 2244.29   123.1 2244.01   133.8 2241.17   136.0 2240.61   142.5 2240.16
   148.8 2240.42   162.0 2241.19   171.7 2243.35   174.9 2245.31   181.4 2250.74
   184.6 2252.92   191.1 2255.64   197.6 2257.28   210.6 2259.26   233.3 2261.32
   249.7 2261.31   256.2 2262.84   279.1 2266.32   289.0 2268.59   295.5 2269.42
#Mann= 3 , 0 , 0
       0     0.1       0   133.8   0.045       0   148.8     0.1       0
Bank Sta=133.8,148.8
Exp/Cntr=0.3,0.1

Type RM Length L Ch R = 1 ,36052.6,230.1,239.5,249
XS GIS Cut Line= 3
     2036012.111      263860.284     2035825.653      263783.200
     2035658.986      263791.534
#Sta/Elev= 30
       0 2260.07     6.5 2259.42    26.0 2255.70    42.3 2253.24    71.6 2246.86
    78.1 2245.85    94.4 2241.62   104.1 2237.85   110.6 2237.20   143.2 2231.23
   154.2 2230.10   162.7 2229.56   169.2 2230.28   172.5 2230.68   182.2 2234.48
   192.0 2234.81   195.3 2235.64   208.3 2243.35   214.8 2245.08   231.2 2246.89
   247.6 2251.18   267.2 2254.41   283.6 2256.36   293.4 2256.58   303.2 2257.90
   316.3 2258.83   332.6 2261.15   339.2 2262.88   355.6 2268.43   368.6 2274.18
#Mann= 3 , 0 , 0
       0     0.1       0   154.2   0.045       0   169.2     0.1       0
Bank Sta=154.2,169.2
Exp/Cntr=0.3,0.1

Type RM Length L Ch R = 1 ,35813.1,315.2,297.4,277.8
XS GIS Cut Line= 3
     2036112.155      263721.872     2035959.160      263561.282
     2035769.273      263558.027
#Sta/Elev= 30
       0 2270.89    22.8 2264.16    32.6 2259.98    35.9 2259.22    45.7 2258.84
    48.9 2257.91    65.2 2250.84    75.0 2244.68    94.6 2228.65    97.8 2226.57
   101.1 2225.28   117.4 2223.56   127.2 2221.20   137.0 2221.50   146.8 2220.81
   158.7 2218.11   169.6 2217.70   173.7 2217.88   179.4 2219.05   192.4 2226.58
   199.0 2228.60   205.5 2229.50   215.3 2229.36   257.8 2232.41   267.6 2232.52
   280.7 2236.38   306.9 2240.62   343.0 2243.59   385.5 2246.22   411.7 2250.08
#Mann= 3 , 0 , 0
       0     0.1       0   158.7   0.045       0   173.7     0.1       0
Bank Sta=158.7,173.7
Exp/Cntr=0.3,0.1

Type RM Length L Ch R = 1 ,35515.7,253,255.7,257.4
XS GIS Cut Line= 2
     2036201.130      263347.523     2035844.142      263342.098
#Sta/Elev= 30
       0 2261.91     3.3 2260.76    13.1 2255.37    22.9 2251.32    36.0 2247.00
    42.6 2244.33    72.1 2230.09    75.3 2228.79    85.2 2226.18    88.4 2224.88
    91.7 2223.06   101.5 2214.75   111.4 2208.56   114.6 2207.40   132.5 2206.62
   134.3 2206.60   147.5 2207.55   150.7 2208.28   160.5 2213.10   167.0 2214.62
   196.5 2218.35   209.6 2219.36   248.9 2225.42   252.2 2226.23   258.8 2228.76
   275.1 2233.57   291.5 2239.61   311.2 2241.61   327.6 2245.85   357.0 2251.18
#Mann= 3 , 0 , 0
       0     0.1       0   132.5   0.045       0   147.5     0.1       0
Bank Sta=132.5,147.5
Exp/Cntr=0.3,0.1

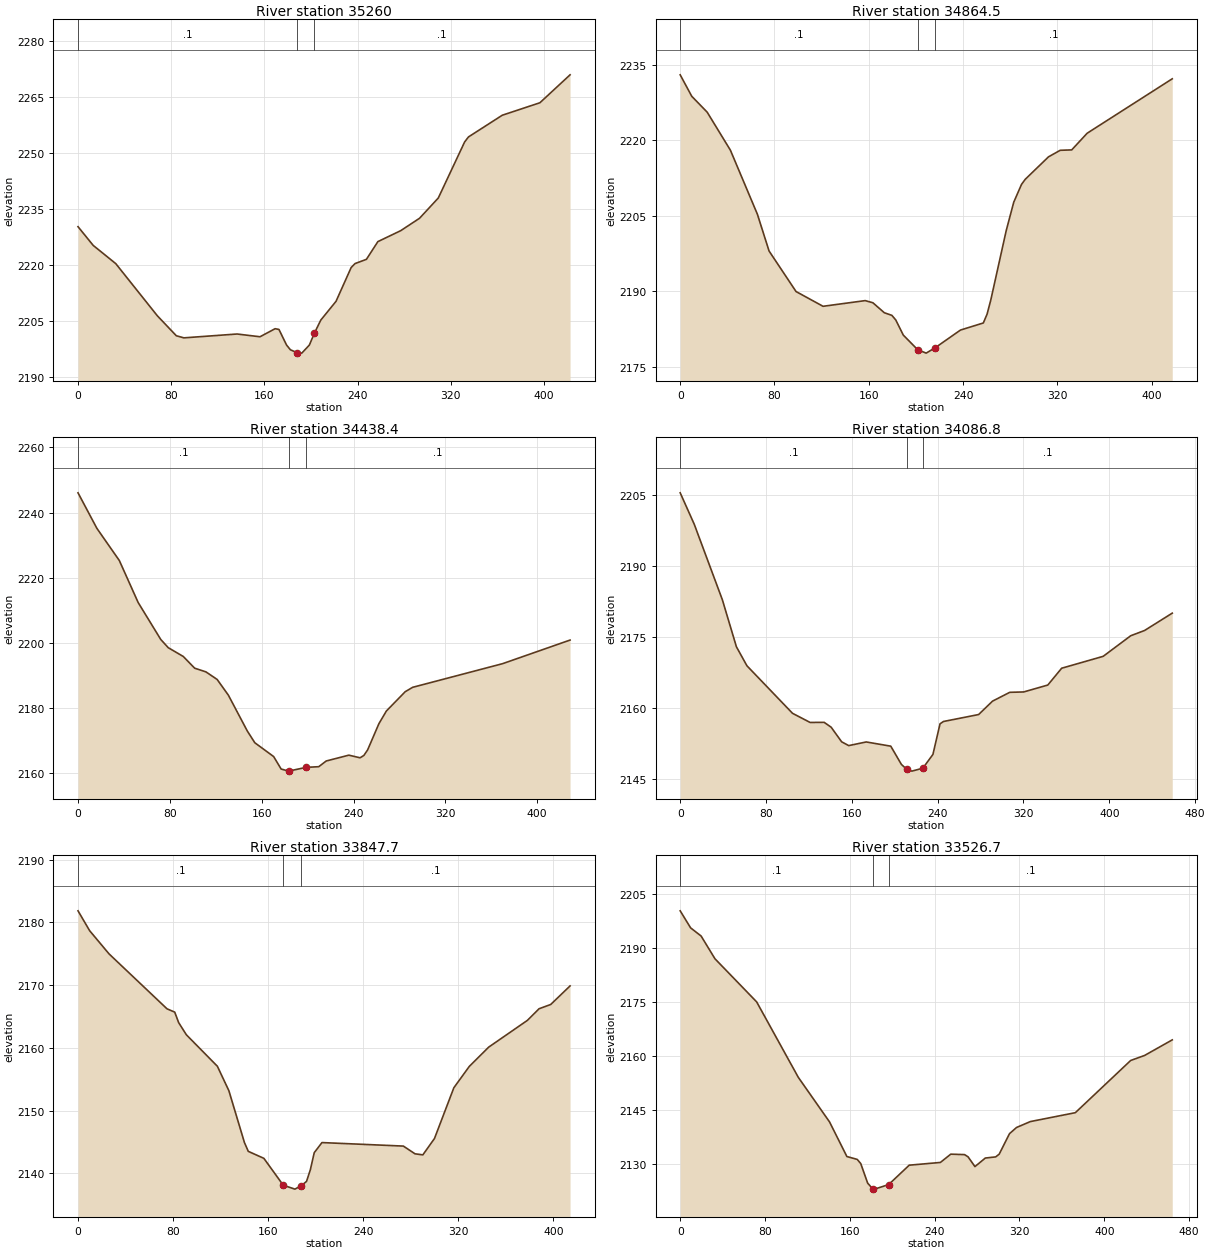
Type RM Length L Ch R = 1 ,35260,396.9,395.5,391.4
XS GIS Cut Line= 4
     2036203.300      263146.785     2036148.275      263119.216
     2035927.693      263094.702     2035788.804      263094.702
#Sta/Elev= 30
       0 2230.28    13.0 2225.28    32.4 2220.39    68.1 2206.42    84.4 2201.07
    90.9 2200.51   136.6 2201.54   156.2 2200.80   169.2 2202.96   172.5 2202.76
   179.0 2198.60   182.3 2197.32   187.9 2196.56   192.1 2196.42   198.6 2198.58
   202.9 2201.75   208.4 2205.26   221.5 2210.30   234.5 2219.35   237.8 2220.40
   247.6 2221.54   257.4 2226.28   277.0 2229.21   293.2 2232.54   309.3 2237.97
   331.9 2252.98   335.2 2254.32   364.2 2260.13   396.5 2263.47   422.4 2270.95
#Mann= 3 , 0 , 0
       0     0.1       0   187.9   0.045       0   202.9     0.1       0
Bank Sta=187.9,202.9
Exp/Cntr=0.3,0.1

Type RM Length L Ch R = 1 ,34864.5,406.6,426.1,444.1
XS GIS Cut Line= 4
     2036295.531      262889.624     2036210.896      262781.117
     2036062.241      262781.117     2035970.010      262687.801
#Sta/Elev= 30
       0 2233.02     9.8 2228.76    22.9 2225.60    42.6 2218.05    65.5 2205.33
    75.4 2198.03    98.3 2189.98   121.2 2187.05   157.0 2188.18   163.5 2187.75
   173.2 2185.77   179.6 2185.25   182.9 2184.34   189.3 2181.33   201.5 2178.43
   208.7 2177.75   216.5 2178.84   237.8 2182.33   257.2 2183.74   260.4 2185.50
   263.6 2188.37   276.6 2202.06   283.0 2207.72   289.6 2211.26   292.8 2212.28
   312.5 2216.73   322.4 2218.03   332.2 2218.11   345.3 2221.42   417.5 2232.23
#Mann= 3 , 0 , 0
       0     0.1       0   201.5   0.045       0   216.5     0.1       0
Bank Sta=201.5,216.5
Exp/Cntr=0.3,0.1

Type RM Length L Ch R = 1 ,34438.4,354.3,351.5,348.3
XS GIS Cut Line= 3
     2036587.415      262710.587     2036402.953      262515.275
     2036243.448      262527.211
#Sta/Elev= 30
       0 2246.06    16.4 2235.18    36.0 2225.28    52.4 2212.39    72.1 2201.05
    78.6 2198.54    91.7 2195.84   101.6 2192.25   111.4 2191.12   121.2 2188.79
   131.0 2183.95   147.4 2173.01   154.0 2169.37   170.4 2165.13   176.9 2161.31
   183.5 2160.66   183.7 2160.68   198.7 2161.82   209.7 2162.02   216.2 2163.77
   235.9 2165.56   245.7 2164.75   249.0 2165.48   252.3 2167.20   262.1 2175.22
   268.6 2179.11   285.0 2185.03   291.5 2186.38   369.8 2193.63   428.6 2200.88
#Mann= 3 , 0 , 0
       0     0.1       0   183.7   0.045       0   198.7     0.1       0
Bank Sta=183.7,198.7
Exp/Cntr=0.3,0.1

Type RM Length L Ch R = 1 ,34086.8,238.4,239.1,237.2
XS GIS Cut Line= 3
     2036758.856      262395.917     2036537.502      262216.881
     2036364.976      262239.667
#Sta/Elev= 30
       0 2205.39    13.1 2198.75    39.3 2182.81    52.4 2172.88    62.2 2168.87
   104.7 2158.83   121.1 2156.90   134.2 2156.92   140.7 2155.90   150.5 2152.81
   157.1 2152.01   173.4 2152.78   196.3 2151.89   206.2 2148.04   211.2 2147.00
   216.0 2146.62   226.2 2147.24   235.6 2150.15   242.2 2156.60   245.4 2157.10
   278.2 2158.57   291.1 2161.39   307.2 2163.26   320.2 2163.34   342.7 2164.80
   355.6 2168.35   394.3 2170.86   420.0 2175.21   432.9 2176.32   458.7 2179.98
#Mann= 3 , 0 , 0
       0     0.1       0   211.2   0.045       0   226.2     0.1       0
Bank Sta=211.2,226.2
Exp/Cntr=0.3,0.1

Type RM Length L Ch R = 1 ,33847.7,326.2,321,314.6
XS GIS Cut Line= 3
     2036799.004      262226.646     2036765.366      262100.778
     2036537.502      261931.508
#Sta/Elev= 30
       0 2181.86     9.8 2178.69    26.1 2175.00    74.9 2166.24    81.4 2165.71
    84.7 2164.04    91.2 2162.10   117.3 2157.08   127.0 2153.17   140.1 2144.90
   143.3 2143.52   156.4 2142.41   172.7 2138.13   182.5 2137.50   187.7 2138.02
   192.3 2138.73   195.5 2140.57   198.8 2143.31   205.3 2144.92   273.8 2144.36
   283.6 2143.13   290.2 2142.96   300.0 2145.57   316.3 2153.66   329.3 2157.06
   345.6 2160.13   378.2 2164.40   388.0 2166.25   397.8 2166.93   414.1 2169.89
#Mann= 3 , 0 , 0
       0     0.1       0   172.7   0.045       0   187.7     0.1       0
Bank Sta=172.7,187.7
Exp/Cntr=0.3,0.1

Type RM Length L Ch R = 1 ,33526.7,258.1,260.9,263.6
XS GIS Cut Line= 3
     2037111.504      261986.846     2037012.762      261895.700
     2036708.943      261767.662
#Sta/Elev= 30
       0 2200.22     9.8 2195.50    19.7 2193.24    32.8 2186.92    72.1 2174.97
   111.4 2154.04   140.9 2141.66   157.2 2132.08   167.0 2131.28   170.3 2130.12
   176.8 2124.71   181.6 2123.10   183.3 2123.04   196.6 2124.30   216.0 2129.68
   245.4 2130.44   255.2 2132.74   268.2 2132.61   271.5 2132.00   278.0 2129.29
   287.8 2131.66   297.6 2131.98   300.9 2132.75   310.6 2138.42   317.2 2140.13
   330.2 2141.77   372.7 2144.24   424.9 2158.72   438.0 2160.11   464.1 2164.43
#Mann= 3 , 0 , 0
       0     0.1       0   181.6   0.045       0   196.6     0.1       0
Bank Sta=181.6,196.6
Exp/Cntr=0.3,0.1

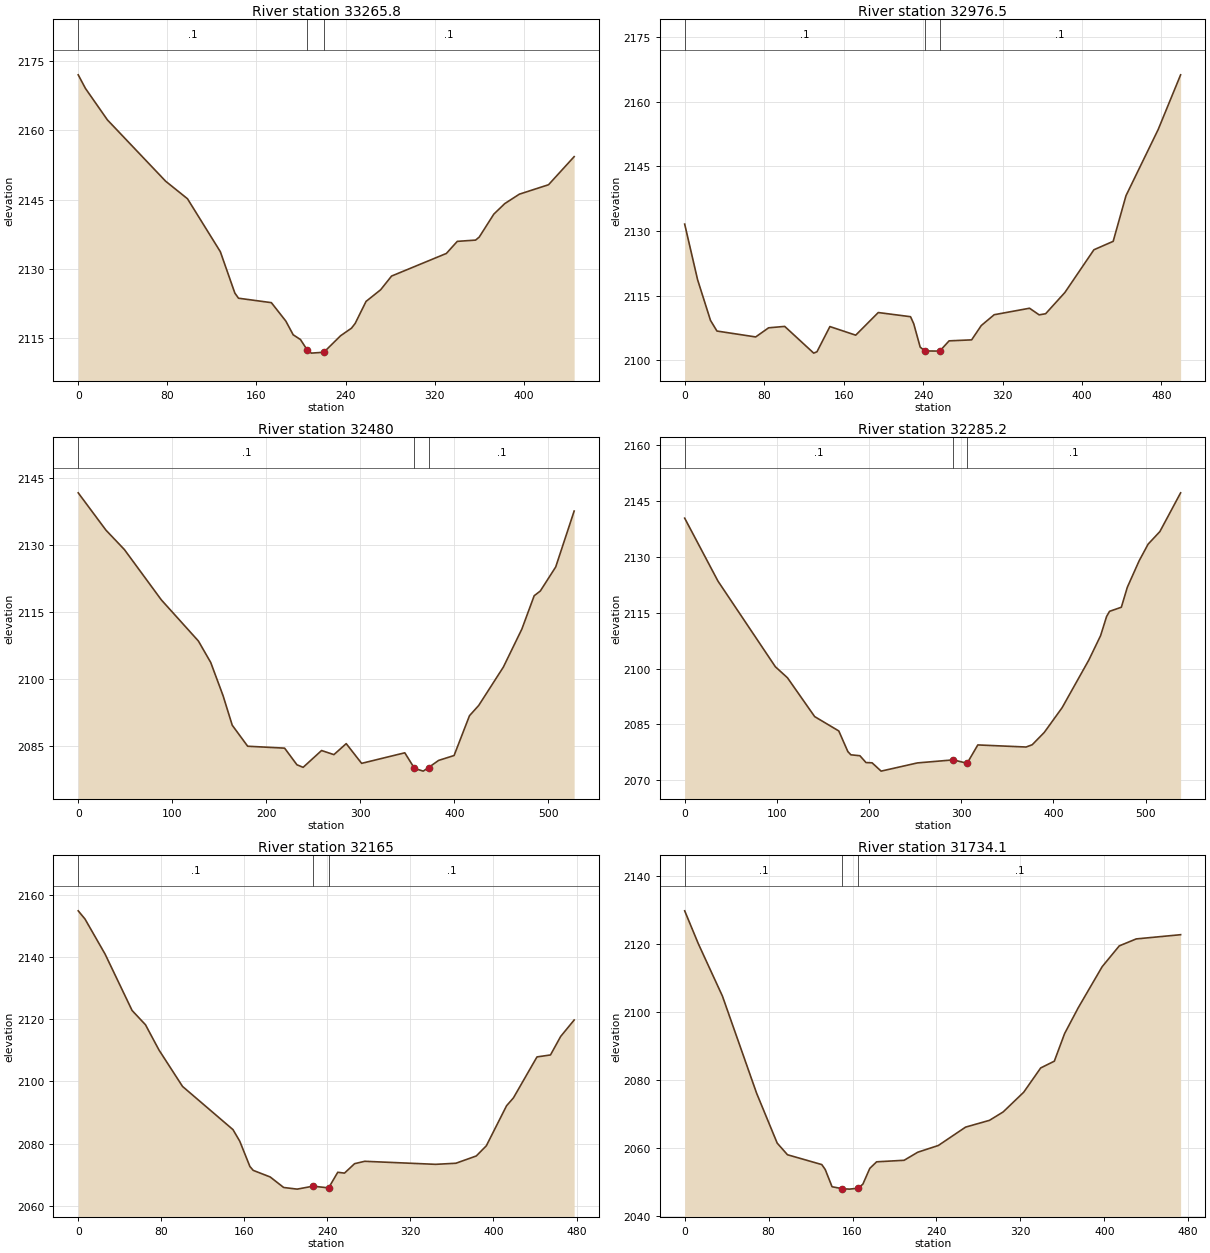
Type RM Length L Ch R = 1 ,33265.8,303.6,289.3,272.9
XS GIS Cut Line= 3
     2037238.240      261737.714     2037009.073      261611.412
     2036830.688      261654.381
#Sta/Elev= 30
       0 2171.96     6.5 2169.02    26.2 2162.22    78.5 2148.96    98.1 2145.17
   127.6 2133.72   140.6 2124.79   143.9 2123.67   173.4 2122.71   186.4 2118.72
   193.0 2115.76   199.5 2114.74   205.5 2112.52   209.3 2111.80   220.5 2111.99
   235.5 2115.55   245.3 2117.19   248.6 2118.21   258.4 2122.98   271.5 2125.50
   281.3 2128.46   330.5 2133.35   340.3 2135.96   356.7 2136.23   360.0 2136.89
   373.1 2141.85   382.9 2144.12   396.0 2146.16   422.2 2148.20   445.2 2154.27
#Mann= 3 , 0 , 0
       0     0.1       0   205.5   0.045       0   220.5     0.1       0
Bank Sta=205.5,220.5
Exp/Cntr=0.3,0.1

Type RM Length L Ch R = 1 ,32976.5,485.3,496.5,508.4
XS GIS Cut Line= 4
     2037352.654      261474.274     2037170.362      261361.427
     2036983.730      261383.128     2036896.925      261339.725
#Sta/Elev= 30
       0 2131.60    13.0 2118.69    26.0 2109.23    32.5 2106.76    71.5 2105.39
    84.5 2107.51   100.7 2107.84   129.9 2101.63   133.2 2101.95   146.2 2107.80
   172.2 2105.80   194.9 2111.06   227.4 2110.09   230.6 2108.46   237.1 2103.03
   241.8 2102.14   256.8 2102.10   266.2 2104.48   288.9 2104.71   298.6 2108.04
   311.6 2110.55   347.2 2112.06   356.9 2110.52   363.4 2110.78   382.8 2115.72
   412.0 2125.64   431.4 2127.60   444.3 2138.20   476.7 2153.57   499.3 2166.28
#Mann= 3 , 0 , 0
       0     0.1       0   241.8   0.045       0   256.8     0.1       0
Bank Sta=241.8,256.8
Exp/Cntr=0.3,0.1

Type RM Length L Ch R = 1 ,32480,193.7,194.8,195.2
XS GIS Cut Line= 2
     2037574.177      261050.214     2037080.688      260864.016
#Sta/Elev= 30
       0 2141.61    29.5 2133.26    49.1 2128.92    88.4 2117.66   127.8 2108.46
   140.9 2103.67   154.0 2096.26   163.8 2089.62   180.2 2084.92   219.5 2084.49
   232.6 2080.77   239.2 2080.20   258.8 2083.96   271.9 2083.04   285.0 2085.50
   301.4 2081.09   347.3 2083.45   357.6 2079.97   366.9 2079.35   372.6 2080.16
   383.3 2081.75   399.7 2082.84   416.1 2091.75   425.9 2094.04   452.1 2102.62
   471.8 2111.13   484.9 2118.59   491.4 2119.64   507.8 2125.03   527.4 2137.53
#Mann= 3 , 0 , 0
       0     0.1       0   357.6   0.045       0   372.6     0.1       0
Bank Sta=357.6,372.6
Exp/Cntr=0.3,0.1

Type RM Length L Ch R = 1 ,32285.2,124.9,120.2,115.3
XS GIS Cut Line= 3
     2037612.224      260880.784     2037251.981      260731.045
     2037105.497      260710.428
#Sta/Elev= 30
       0 2140.37    36.1 2123.48    98.4 2100.48   111.5 2097.53   141.0 2087.11
   167.2 2083.25   177.0 2077.72   180.3 2076.85   190.1 2076.60   196.7 2074.77
   203.3 2074.70   213.1 2072.47   252.4 2074.67   291.4 2075.49   306.4 2074.58
   318.0 2079.50   370.4 2078.94   377.0 2079.55   390.1 2082.86   409.4 2089.48
   438.4 2102.28   451.2 2108.84   457.7 2113.98   460.9 2115.36   473.7 2116.46
   480.2 2121.83   493.0 2128.92   502.7 2133.38   515.5 2136.77   538.0 2147.17
#Mann= 3 , 0 , 0
       0     0.1       0   291.4   0.045       0   306.4     0.1       0
Bank Sta=291.4,306.4
Exp/Cntr=0.3,0.1

Type RM Length L Ch R = 1 ,32165,430.8,430.9,430.5
XS GIS Cut Line= 3
     2037637.979      260686.933     2037489.542      260701.256
     2037178.344      260595.787
#Sta/Elev= 30
       0 2154.99     6.5 2152.37    25.9 2141.04    51.9 2122.87    64.8 2118.27
    77.8 2110.14   100.5 2098.39   149.1 2084.47   155.6 2080.75   165.4 2072.58
   168.6 2071.34   184.9 2069.22   197.9 2065.83   210.9 2065.30   226.2 2066.25
   241.2 2065.70   250.0 2070.73   256.5 2070.46   266.2 2073.50   276.0 2074.27
   344.3 2073.29   363.8 2073.64   383.4 2075.98   393.1 2079.26   412.6 2092.17
   419.2 2094.70   441.9 2107.91   454.9 2108.54   464.7 2114.50   477.7 2119.80
#Mann= 3 , 0 , 0
       0     0.1       0   226.2   0.045       0   241.2     0.1       0
Bank Sta=226.2,241.2
Exp/Cntr=0.3,0.1

Type RM Length L Ch R = 1 ,31734.1,282.2,269,255.9
XS GIS Cut Line= 3
     2037664.021      260300.214     2037427.042      260252.037
     2037208.292      260326.256
#Sta/Elev= 30
       0 2129.62    13.1 2119.88    36.0 2104.54    68.6 2075.97    88.2 2061.32
    98.0 2057.90   130.7 2055.01   134.0 2053.56   140.5 2048.49   150.3 2047.92
   156.9 2047.79   165.3 2048.05   169.9 2049.26   176.5 2053.90   183.0 2055.82
   209.2 2056.27   222.2 2058.64   241.8 2060.62   267.8 2066.02   290.6 2068.02
   303.6 2070.48   323.2 2076.28   339.4 2083.42   352.4 2085.41   362.2 2093.53
   375.2 2101.12   398.0 2113.19   414.3 2119.31   430.5 2121.36   472.8 2122.60
#Mann= 3 , 0 , 0
       0     0.1       0   150.3   0.045       0   165.3     0.1       0
Bank Sta=150.3,165.3
Exp/Cntr=0.3,0.1

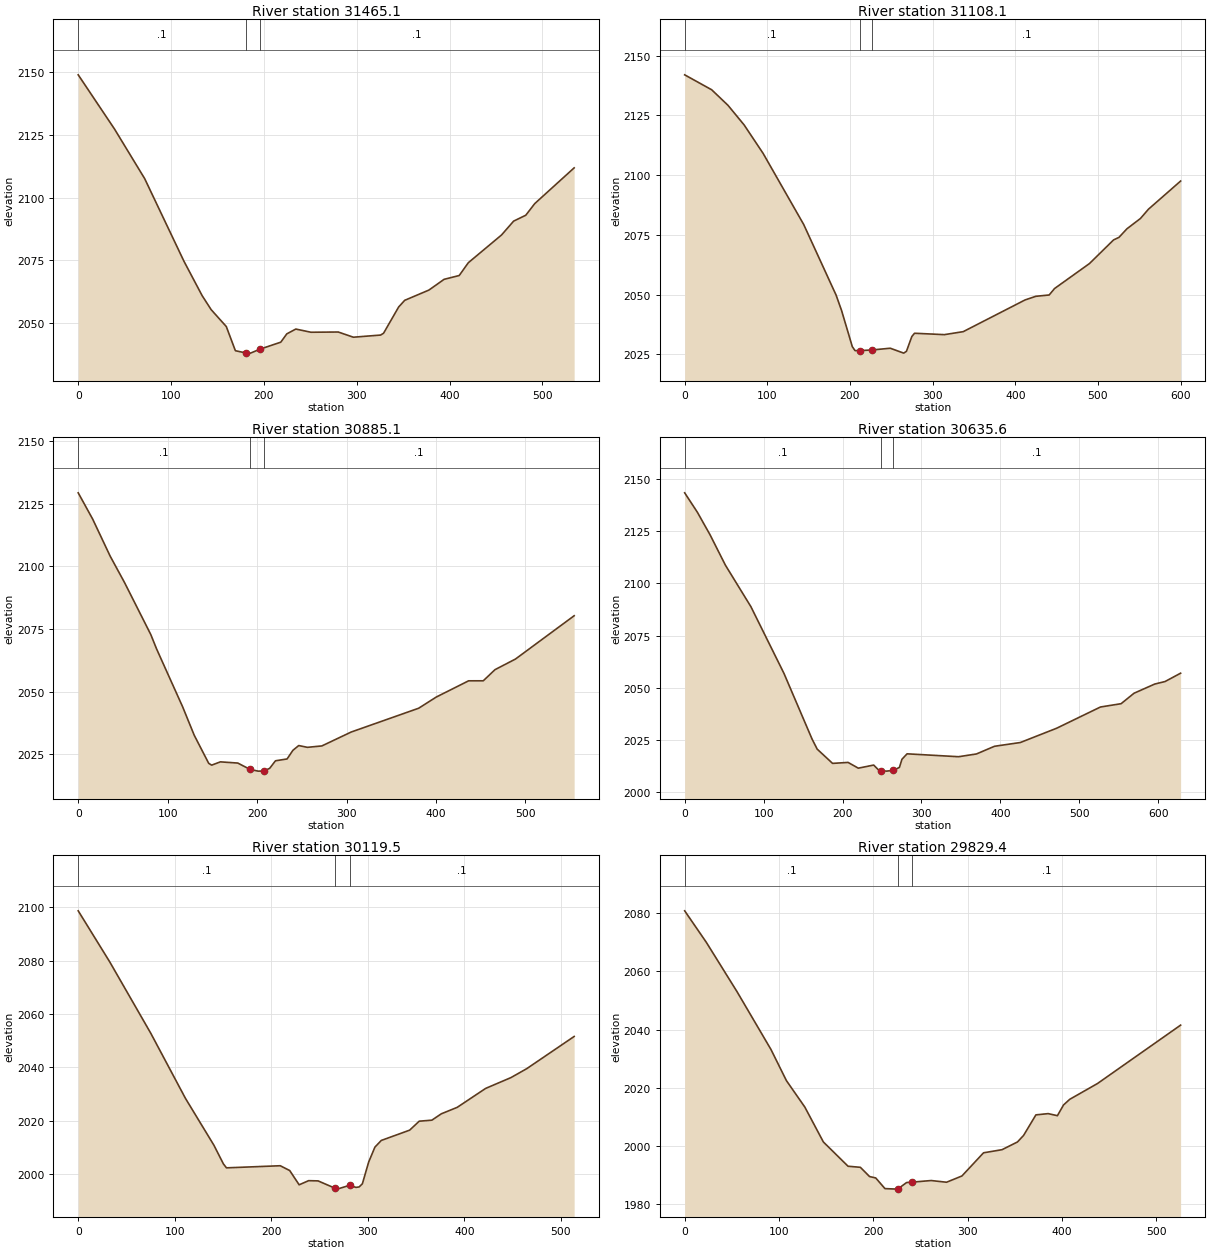
Type RM Length L Ch R = 1 ,31465.1,336.2,357,377.8
XS GIS Cut Line= 3
     2037697.875      259986.412     2037548.135      259987.714
     2037191.365      260130.943
#Sta/Elev= 30
       0 2148.95    39.1 2127.35    71.6 2107.59   113.9 2074.68   133.5 2060.97
   143.2 2055.39   159.5 2048.67   169.3 2039.03   180.8 2038.13   185.6 2038.07
   195.8 2039.65   218.2 2042.43   224.7 2045.75   234.4 2047.66   250.7 2046.39
   280.1 2046.48   296.4 2044.41   325.7 2045.27   328.9 2045.99   345.2 2056.47
   351.7 2059.11   377.8 2063.20   394.1 2067.47   410.4 2068.99   420.2 2074.09
   456.0 2085.15   469.0 2090.66   482.1 2093.01   491.8 2097.66   534.2 2111.88
#Mann= 3 , 0 , 0
       0     0.1       0   180.8   0.045       0   195.8     0.1       0
Bank Sta=180.8,195.8
Exp/Cntr=0.3,0.1

Type RM Length L Ch R = 1 ,31108.1,233.6,223,211.4
XS GIS Cut Line= 3
     2037710.896      259813.235     2037403.604      259632.245
     2037164.021      259675.214
#Sta/Elev= 30
       0 2141.92    32.7 2135.66    52.4 2129.17    72.0 2120.93    94.9 2109.06
   144.0 2079.33   183.2 2049.79   189.8 2043.37   202.8 2028.25   206.1 2026.58
   211.6 2026.57   226.6 2026.85   248.7 2027.58   265.0 2025.53   268.3 2026.29
   274.8 2032.46   278.1 2033.84   314.1 2033.26   337.0 2034.51   411.8 2047.77
   424.8 2049.29   441.0 2049.85   447.5 2052.55   489.7 2062.98   518.9 2072.88
   525.4 2073.94   535.1 2077.54   551.4 2081.84   561.1 2085.72   600.0 2097.50
#Mann= 3 , 0 , 0
       0     0.1       0   211.6   0.045       0   226.6     0.1       0
Bank Sta=211.6,226.6
Exp/Cntr=0.3,0.1

Type RM Length L Ch R = 1 ,30885.1,249.8,249.5,248.4
XS GIS Cut Line= 3
     2037757.771      259502.037     2037479.125      259490.318
     2037209.594      259547.610
#Sta/Elev= 30
       0 2129.40    16.2 2118.89    35.7 2104.14    51.9 2093.50    81.1 2072.85
    87.6 2067.09   116.8 2043.92   129.7 2032.62   145.9 2021.40   149.2 2020.69
   158.9 2022.00   178.4 2021.52   192.2 2018.97   201.1 2018.30   207.2 2018.33
   214.0 2019.40   220.5 2022.42   233.5 2023.16   240.0 2026.60   246.5 2028.51
   256.2 2027.80   272.4 2028.36   305.1 2033.90   380.6 2043.41   400.3 2047.88
   436.4 2054.35   452.8 2054.36   465.9 2058.80   488.8 2063.04   554.4 2080.33
#Mann= 3 , 0 , 0
       0     0.1       0   192.2   0.045       0   207.2     0.1       0
Bank Sta=192.2,207.2
Exp/Cntr=0.3,0.1

Type RM Length L Ch R = 1 ,30635.6,498.3,516.1,528.2
XS GIS Cut Line= 4
     2037829.385      259202.558     2037679.646      259253.339
     2037451.781      259249.433     2037238.240      259364.016
#Sta/Elev= 30
       0 2143.47    16.1 2134.15    32.3 2123.24    51.6 2108.78    83.9 2088.88
   125.8 2056.88   161.4 2025.39   167.9 2020.55   187.4 2013.71   207.0 2014.18
   220.0 2011.42   239.5 2012.91   246.0 2010.42   249.3 2010.20   255.8 2010.00
   264.3 2010.36   272.1 2011.79   275.3 2015.69   281.8 2018.30   347.0 2016.91
   369.7 2018.23   392.6 2021.92   425.3 2023.72   471.2 2030.55   526.8 2040.75
   553.0 2042.34   569.4 2047.36   595.6 2051.76   608.7 2052.97   628.4 2056.97
#Mann= 3 , 0 , 0
       0     0.1       0   249.3   0.045       0   264.3     0.1       0
Bank Sta=249.3,264.3
Exp/Cntr=0.3,0.1

Type RM Length L Ch R = 1 ,30119.5,296.4,290.1,284.2
XS GIS Cut Line= 4
     2037708.292      258891.360     2037565.063      258878.339
     2037386.677      258762.454     2037230.427      258744.225
#Sta/Elev= 30
       0 2098.73    32.7 2079.56    75.2 2052.80   111.1 2028.40   140.6 2010.82
   150.4 2003.84   153.6 2002.34   209.3 2003.13   219.1 2001.34   228.9 1995.98
   238.7 1997.53   248.5 1997.45   266.1 1994.70   268.2 1994.36   281.1 1995.77
   287.8 1995.01   291.1 1995.19   294.4 1996.37   300.9  2004.5   307.4 2010.12
   314.0 2012.62   343.4 2016.48   353.3 2019.84   366.4 2020.22   376.2 2022.61
   392.6 2025.02   422.1 2032.13   448.3 2036.18   464.7 2039.54   513.8 2051.61
#Mann= 3 , 0 , 0
       0     0.1       0   266.1   0.045       0   281.1     0.1       0
Bank Sta=266.1,281.1
Exp/Cntr=0.3,0.1

Type RM Length L Ch R = 1 ,29829.4,320.4,329.2,337.3
XS GIS Cut Line= 3
     2037740.844      258725.995     2037683.552      258590.579
     2037320.271      258483.808
#Sta/Elev= 30
       0 2080.81    22.9 2070.01    55.6 2052.98    91.5 2033.16   107.8 2022.50
   127.4 2013.37   147.0 2001.41   173.2 1993.06   186.2 1992.70   196.0 1989.52
   202.5 1989.04   212.3 1985.38   225.4 1985.20   226.3 1985.32   235.2 1987.46
   241.3 1987.61   261.3 1988.15   277.6 1987.57   293.9 1989.72   316.8 1997.68
   336.4 1998.75   352.7 2001.39   359.2 2003.63   372.3 2010.71   385.3 2011.14
   395.1 2010.43   401.6 2014.12   408.2 2016.06   437.6 2021.48   525.7 2041.54
#Mann= 3 , 0 , 0
       0     0.1       0   226.3   0.045       0   241.3     0.1       0
Bank Sta=226.3,241.3
Exp/Cntr=0.3,0.1