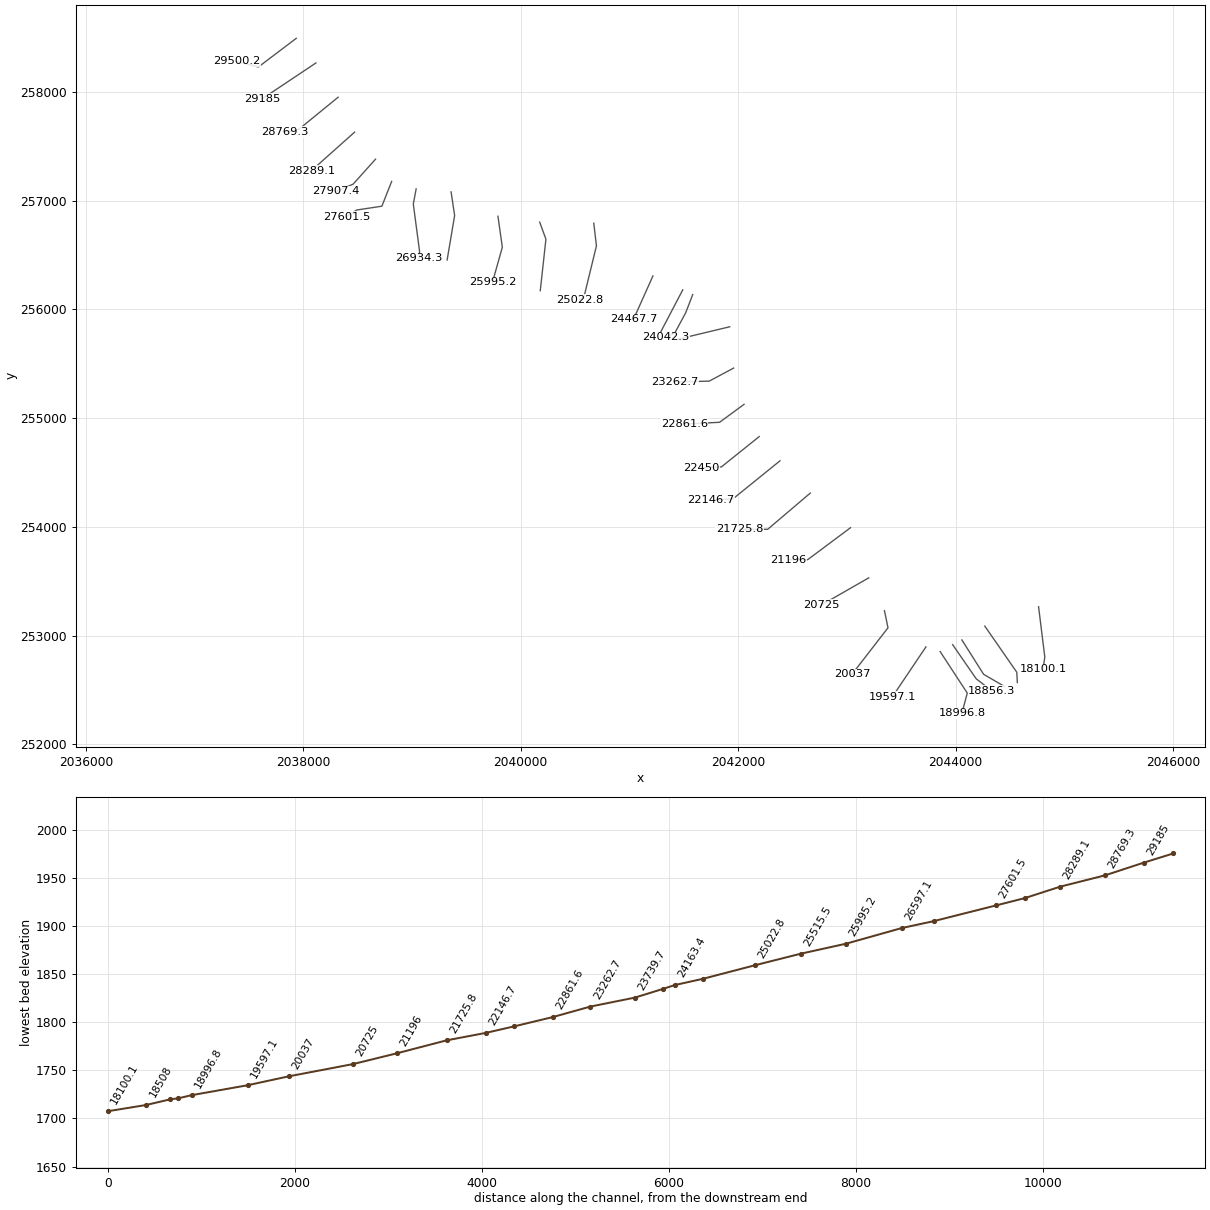
HEC-RAS study HNGRDCK.prj: HNGRDCK

--- HNGRDCK.g01 (geometry) --- (continued)

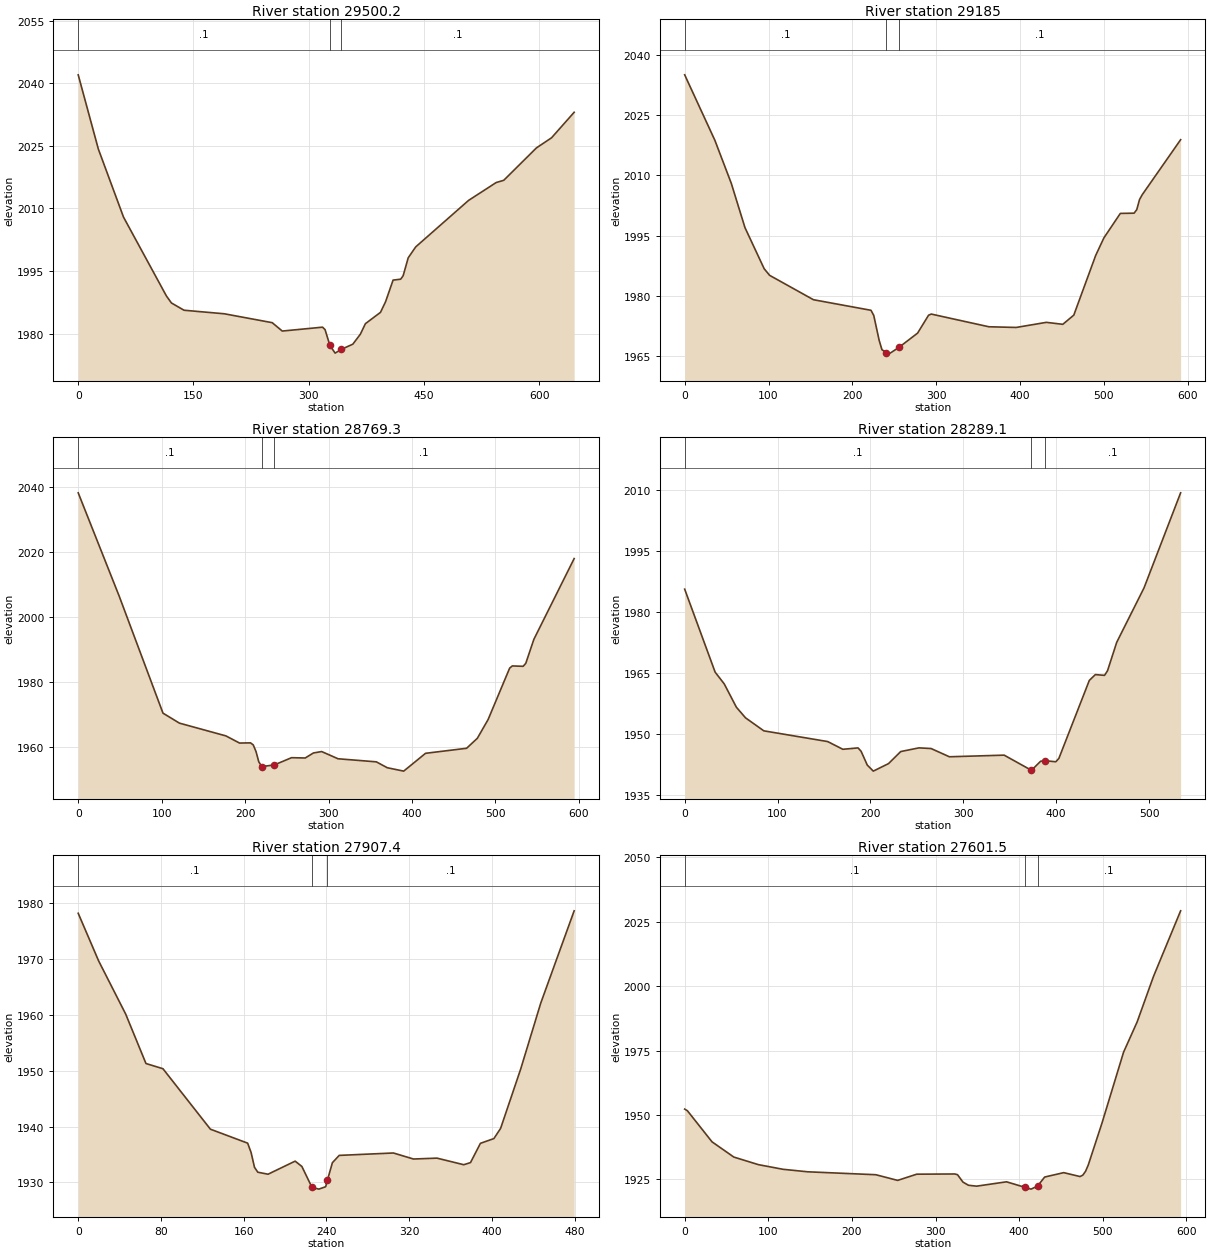
Type RM Length L Ch R = 1 ,29500.2,316.4,315.1,312.9
XS GIS Cut Line= 3
     2037934.854      258494.225     2037587.198      258231.204
     2037384.073      258281.985
#Sta/Elev= 30
       0 2042.00    26.2 2024.21    59.0 2007.88   114.7 1989.02   121.3 1987.32
   137.7 1985.58   190.1 1984.73   252.4 1982.60   265.5 1980.59   317.9 1981.52
   321.2 1980.93   327.5 1977.14   334.3 1975.30   342.5 1976.22   357.3 1977.44
   367.1 1979.83   373.7 1982.36   393.3 1985.07   399.9 1987.61   409.7 1992.80
   419.6 1993.02   422.8 1993.85   429.4 1998.15   439.2 2000.77   507.9 2011.90
   543.9 2016.19   553.7 2016.72   596.2 2024.48   615.9 2026.91   645.3 2033.02
#Mann= 3 , 0 , 0
       0     0.1       0   327.5   0.045       0   342.5     0.1       0
Bank Sta=327.5,342.5
Exp/Cntr=0.3,0.1

Type RM Length L Ch R = 1 ,29185,413.5,415.7,417.5
XS GIS Cut Line= 2
     2038115.844      258267.662     2037623.656      257939.537
#Sta/Elev= 30
       0 2035.04    36.0 2018.75    55.6 2008.03    71.9 1997.02    94.8 1986.79
   101.3 1985.14   153.6 1979.07   222.2 1976.44   225.5 1975.17   232.0 1968.92
   235.3 1966.63   240.5 1965.92   245.1 1965.78   255.5 1967.20   277.8 1970.76
   290.9 1975.22   294.1 1975.50   362.8 1972.34   395.4 1972.17   431.4 1973.44
   451.0 1972.95   464.1 1975.24   490.2 1990.09   500.0 1994.46   519.6 2000.55
   536.0 2000.61   539.2 2001.49   542.5 2004.01   545.8 2005.23   591.5 2018.89
#Mann= 3 , 0 , 0
       0     0.1       0   240.5   0.045       0   255.5     0.1       0
Bank Sta=240.5,255.5
Exp/Cntr=0.3,0.1

Type RM Length L Ch R = 1 ,28769.3,478.4,480.2,480.3
XS GIS Cut Line= 3
     2038320.271      257952.558     2037959.594      257658.287
     2037833.292      257632.245
#Sta/Elev= 30
       0 2038.30    49.2 2006.41   101.6 1970.41   121.3 1967.33   177.0 1963.40
   193.4 1961.19   206.5 1961.25   209.8 1960.62   213.1 1958.58   216.4 1955.42
     220 1953.94     235 1954.45   255.7 1956.68   272.1 1956.59   281.9 1958.14
   291.8 1958.57   311.4 1956.35   357.3 1955.40   370.4 1953.59   390.1 1952.54
   416.3 1958.03   465.5 1959.58   478.4 1962.67   491.3 1968.45   517.1 1984.28
   520.3 1984.96   533.2 1984.84   536.4 1985.74   546.1 1993.14   594.4 2018.04
#Mann= 3 , 0 , 0
       0     0.1       0     220   0.045       0     235     0.1       0
Bank Sta=220,235
Exp/Cntr=0.3,0.1

Type RM Length L Ch R = 1 ,28289.1,378.1,381.7,383.8
XS GIS Cut Line= 2
     2038471.313      257630.943     2038072.875      257275.475
#Sta/Elev= 30
       0 1985.52    32.8 1965.11    42.6 1962.22    55.7 1956.48    65.5 1953.88
    85.2 1950.68   154.0 1948.04   170.3 1946.14   186.7 1946.48   190.0 1945.64
   196.6 1942.26   203.1 1940.77   219.5 1942.62   232.6 1945.58   252.2 1946.49
   265.3 1946.33   285.0 1944.30   344.0 1944.70   373.4 1940.97   383.3 1943.21
   388.4 1943.33   399.6 1943.07   402.9 1943.89   435.7 1963.08   442.2 1964.51
   452.1 1964.32   455.3 1965.46   465.2 1972.45   494.6 1985.83   534.0 2009.21
#Mann= 3 , 0 , 0
       0     0.1       0   373.4   0.045       0   388.4     0.1       0
Bank Sta=373.4,388.4
Exp/Cntr=0.3,0.1

Type RM Length L Ch R = 1 ,27907.4,320.2,305.8,289.8
XS GIS Cut Line= 3
     2038664.021      257382.245     2038458.292      257153.079
     2038300.740      257085.370
#Sta/Elev= 30
       0 1978.18    19.7 1969.67    45.9 1960.13    65.5 1951.28    81.9 1950.35
   127.8 1939.52   163.8 1937.02   167.1 1935.36   170.4 1932.70   173.6 1931.82
   183.5 1931.46   209.7 1933.80   216.2 1932.85   225.9 1929.13   232.6 1928.79
   239.2 1929.22   240.9 1930.39   245.7 1933.52   252.3 1934.83   304.7 1935.26
   324.1 1934.18   346.8 1934.34   372.7 1933.16   379.2 1933.54   388.8 1936.99
   401.8 1937.84   408.3 1939.66   427.7 1950.28   447.1 1962.09   479.4 1978.62
#Mann= 3 , 0 , 0
       0     0.1       0   225.9   0.045       0   240.9     0.1       0
Bank Sta=225.9,240.9
Exp/Cntr=0.3,0.1

Type RM Length L Ch R = 1 ,27601.5,633.1,667.2,701.4
XS GIS Cut Line= 4
     2038812.458      257177.818     2038722.615      256949.954
     2038490.844      256914.797     2038395.792      256852.297
#Sta/Elev= 30
       0 1952.33     3.3 1951.68    32.7 1939.62    58.8 1933.70    88.2 1930.76
   117.6 1928.96   147.0 1927.99   228.6 1926.85   254.7 1924.65   277.5 1927.06
   323.1 1927.14   326.3 1926.87   332.8 1923.99   339.4 1922.76   349.1 1922.41
   384.9 1924.10     407 1921.95   414.2 1921.26     422 1922.43   430.5 1925.95
   453.3 1927.66   472.8 1926.14   476.1 1926.67   479.4 1928.18   482.6 1930.58
   498.9 1946.73   524.9 1974.44   541.1 1986.15   560.6 2003.77   593.1 2029.29
#Mann= 3 , 0 , 0
       0     0.1       0     407   0.045       0     422     0.1       0
Bank Sta=407,422
Exp/Cntr=0.3,0.1

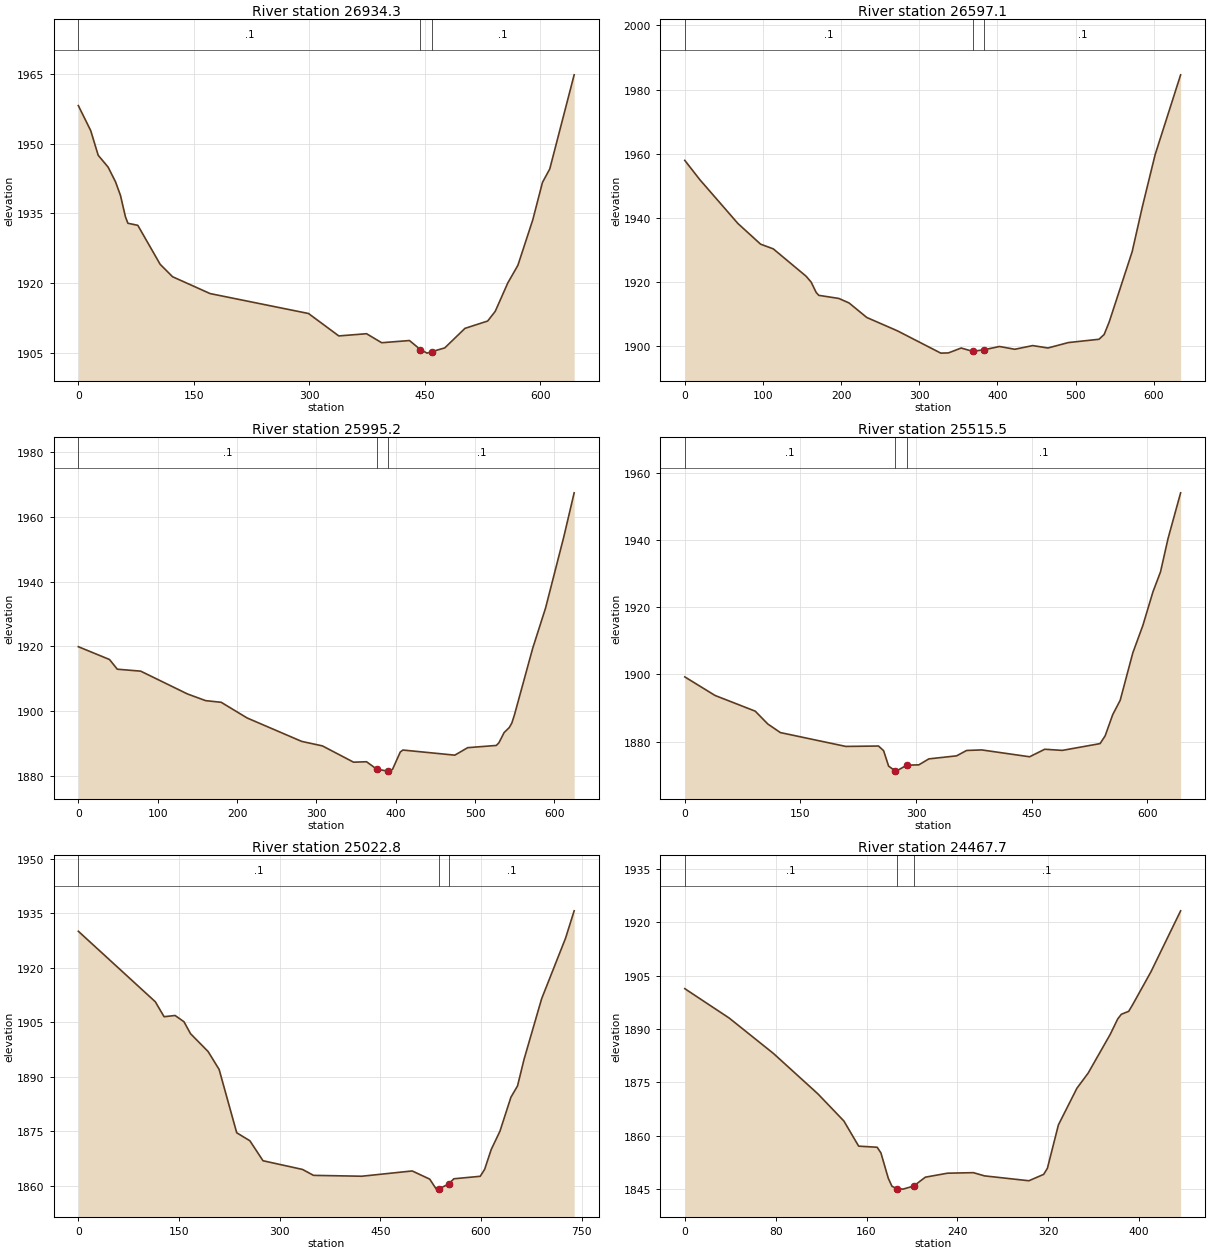
Type RM Length L Ch R = 1 ,26934.3,342.6,337.2,330.5
XS GIS Cut Line= 4
     2039037.719      257108.808     2039011.677      256969.485
     2039068.969      256537.193     2039066.365      256470.787
#Sta/Elev= 30
       0 1958.19    16.1 1952.80    25.8 1947.50    38.7 1944.94    48.3 1941.79
    54.8 1938.82    61.2 1934.26    64.4 1932.86    77.3 1932.41   106.3 1924.03
   122.4 1921.35   171.2 1917.72   299.1 1913.43   338.5 1908.60   374.5 1909.08
   394.2 1907.14   430.3 1907.61   444.5 1905.67   453.2 1904.90   459.5 1905.22
   476.2 1906.03   502.4 1910.23   531.9 1911.81   541.7 1913.88   558.1 1920.02
   571.2 1923.81   590.5 1933.58   603.1 1941.64   612.6 1944.55   644.3 1964.81
#Mann= 3 , 0 , 0
       0     0.1       0   444.5   0.045       0   459.5     0.1       0
Bank Sta=444.5,459.5
Exp/Cntr=0.3,0.1

Type RM Length L Ch R = 1 ,26597.1,603.2,601.9,596.7
XS GIS Cut Line= 3
     2039359.333      257081.464     2039391.885      256864.016
     2039322.875      256455.162
#Sta/Elev= 30
       0 1957.94    19.4 1951.88    67.9 1938.29    97.0 1931.82   113.2 1930.37
   155.2 1921.84   161.7 1920.00   168.1 1916.79   171.4 1915.88   197.2 1914.90
   210.2 1913.50   232.9 1908.97   272.1 1904.81   327.6 1897.86   337.4 1897.93
   353.7 1899.45   368.4 1898.42   383.4 1898.92   402.7 1899.93   422.3 1899.06
   445.2 1900.21   464.7 1899.46   490.8 1901.15   530.0 1902.18   536.6 1903.65
   543.1 1907.57   572.5 1929.49   585.5 1943.46   601.9 1959.75   634.5 1984.61
#Mann= 3 , 0 , 0
       0     0.1       0   368.4   0.045       0   383.4     0.1       0
Bank Sta=368.4,383.4
Exp/Cntr=0.3,0.1

Type RM Length L Ch R = 1 ,25995.2,476.3,479.6,482.8
XS GIS Cut Line= 3
     2039790.323      256857.506     2039830.688      256572.350
     2039739.542      256248.131
#Sta/Elev= 30
       0 1919.93    39.3 1915.97    49.1 1912.97    78.6 1912.37   137.4 1905.33
   160.4 1903.25   180.0 1902.74   212.7 1897.89   281.4 1890.65   307.6 1889.25
   346.8 1884.22   363.2 1884.35   375.8 1882.10   389.4 1881.45   390.8 1881.48
   395.9 1881.99   405.7 1887.36   409.0 1887.97   474.4 1886.39   490.7 1888.71
   526.7 1889.39   530.0 1890.22   536.5 1893.36   543.0 1894.92   546.3 1896.34
   549.6 1898.88   572.5 1919.39   588.8 1931.92   611.7 1953.85   624.8 1967.52
#Mann= 3 , 0 , 0
       0     0.1       0   375.8   0.045       0   390.8     0.1       0
Bank Sta=375.8,390.8
Exp/Cntr=0.3,0.1

Type RM Length L Ch R = 1 ,25515.5,496,492.8,489.4
XS GIS Cut Line= 3
     2040174.438      256802.818     2040231.729      256646.568
     2040179.646      256172.610
#Sta/Elev= 30
       0 1899.23    39.2 1893.71    91.4 1889.03   107.7 1885.21   124.0 1882.66
   208.9 1878.54   251.3 1878.66   257.9 1877.28   264.4 1872.68   273.1 1871.23
   274.2 1871.19   288.1 1872.96   303.6 1873.06   316.6 1874.83   352.6 1875.74
   365.6 1877.34   385.2 1877.50   447.3 1875.46   466.9 1877.70   489.7 1877.36
   538.7 1879.38   545.3 1881.69   555.1 1888.00   564.8 1892.27   581.2 1906.39
   594.2 1914.53   607.3 1924.54   617.1 1930.47   626.9 1940.42   643.2 1954.00
#Mann= 3 , 0 , 0
       0     0.1       0   273.1   0.045       0   288.1     0.1       0
Bank Sta=273.1,288.1
Exp/Cntr=0.3,0.1

Type RM Length L Ch R = 1 ,25022.8,559.2,555,550.7
XS GIS Cut Line= 4
     2040671.833      256793.704     2040696.573      256585.370
     2040581.990      256115.318     2040544.229      256090.579
#Sta/Elev= 30
       0 1930.08   114.7 1910.68   127.8 1906.56   144.2 1906.90   157.4 1905.18
   167.2 1901.89   193.4 1896.98   209.8 1892.05   236.0 1874.63   255.6 1872.43
   275.2 1866.93   334.0 1864.54   350.4 1862.91   422.3 1862.67   497.5 1864.12
   523.6 1861.87   533.4 1859.12     537 1859.14     552 1860.57   559.6 1861.97
   598.8 1862.65   605.4 1864.55   615.2 1870.02   628.2 1875.05   644.6 1884.42
   654.4 1887.51   664.2 1894.88   690.3 1911.49   725.9 1928.13   738.8 1935.70
#Mann= 3 , 0 , 0
       0     0.1       0     537   0.045       0     552     0.1       0
Bank Sta=537,552
Exp/Cntr=0.3,0.1

Type RM Length L Ch R = 1 ,24467.7,305.5,304.4,302.7
XS GIS Cut Line= 2
     2041216.104      256308.027     2041037.719      255909.589
#Sta/Elev= 30
       0 1901.33    39.1 1893.08    78.2 1883.11   117.3 1871.78   140.1 1864.19
   153.1 1857.14   169.4 1856.83   172.7 1855.24   179.2 1848.11   182.4 1845.89
   186.6 1845.25   192.2 1845.08   201.6 1845.96   211.8 1848.43   231.3 1849.55
   254.1 1849.70   263.9 1848.80   303.0 1847.43   316.0 1849.22   319.3 1850.94
   329.0 1863.12   345.3 1873.40   355.1 1877.60   374.6 1888.50   381.2 1892.83
   384.4 1894.14   390.9 1894.98   394.2 1896.75   410.5 1906.08   436.6 1923.17
#Mann= 3 , 0 , 0
       0     0.1       0   186.6   0.045       0   201.6     0.1       0
Bank Sta=186.6,201.6
Exp/Cntr=0.3,0.1

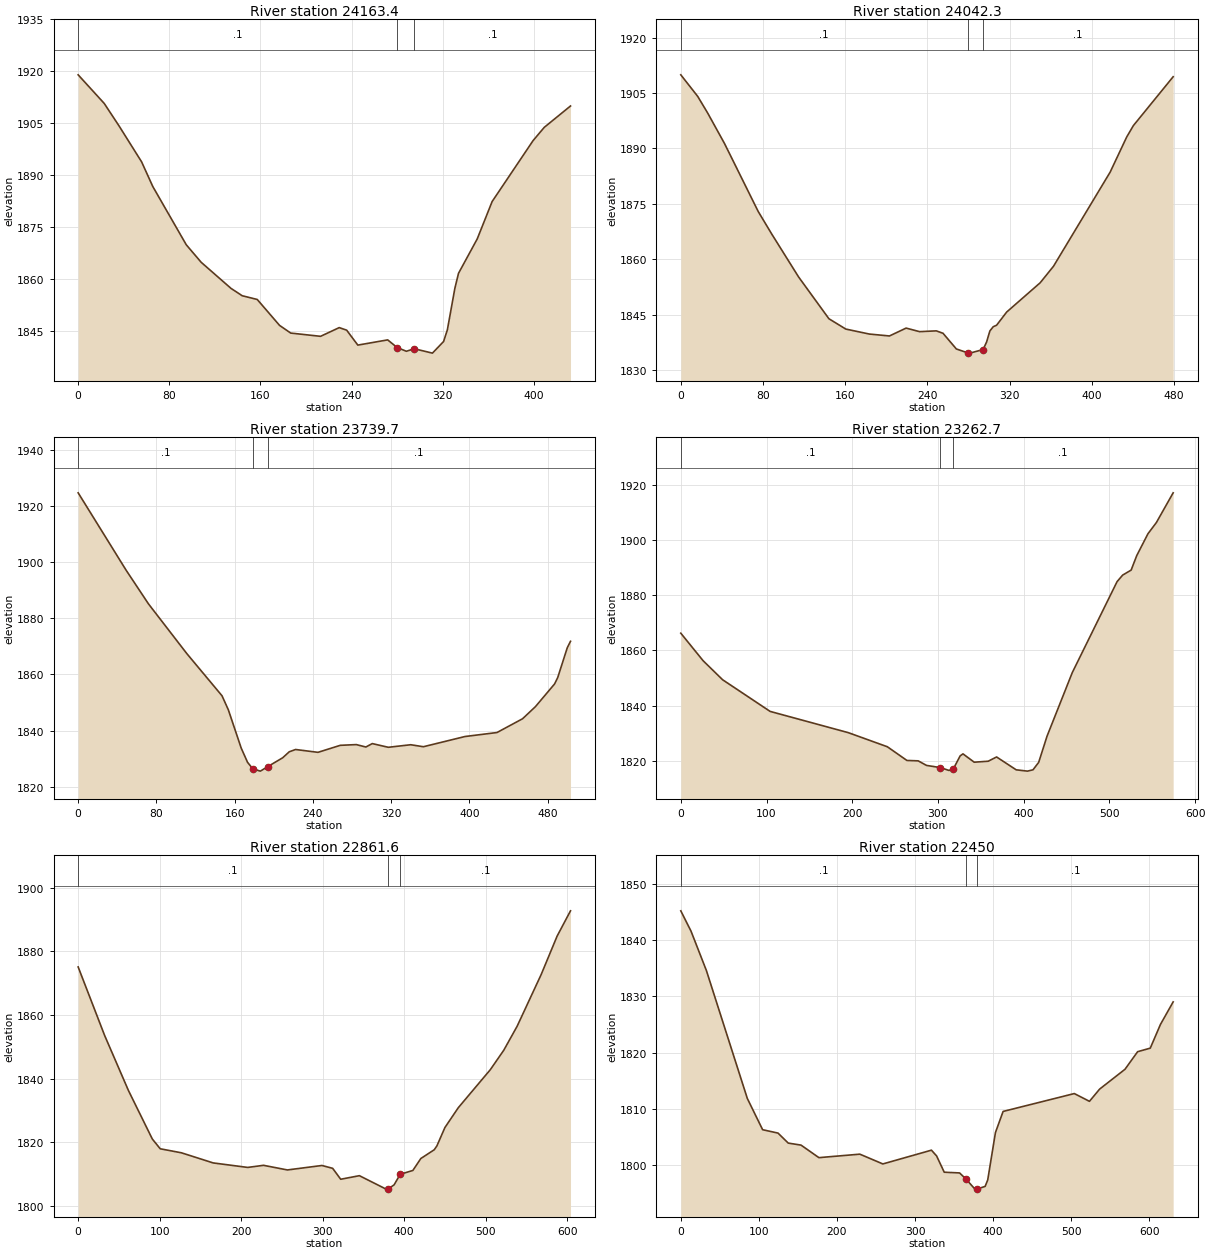
Type RM Length L Ch R = 1 ,24163.4,121.1,121.1,120.5
XS GIS Cut Line= 2
     2041490.844      256180.422     2041290.323      255797.610
#Sta/Elev= 30
       0 1918.99    22.9 1910.71    36.0 1904.16    55.7 1893.82    65.5  1886.7
    94.9 1869.84   108.0 1864.77   134.2 1857.22   144.0 1855.10   157.2 1854.02
   176.8 1846.52   186.6 1844.30   212.8 1843.36   229.2 1845.88   235.7 1845.14
   245.5 1840.82   271.7 1842.33   280.1 1840.10   288.1 1839.04   295.1 1839.76
   311.0 1838.50   320.8 1841.87   324.1 1845.24   330.7 1857.27   333.9 1861.59
   350.3 1871.52   363.4 1882.34   399.4 1899.99   409.2 1903.81   432.2 1909.98
#Mann= 3 , 0 , 0
       0     0.1       0   280.1   0.045       0   295.1     0.1       0
Bank Sta=280.1,295.1
Exp/Cntr=0.3,0.1

Type RM Length L Ch R = 1 ,24042.3,322.1,302.7,282.5
XS GIS Cut Line= 4
     2041582.305      256136.441     2041517.201      255968.472
     2041418.243      255784.878     2041337.513      255744.514
#Sta/Elev= 30
       0 1909.92    16.4 1904.11    26.2 1899.56    42.6 1891.30    75.3 1872.96
    88.4 1866.89   114.6 1855.25   144.1 1843.95   160.5 1841.16   183.4 1839.81
   203.0 1839.29   219.2 1841.42   232.3 1840.46   248.6 1840.67   255.1 1840.02
   268.1 1835.77   279.1 1834.73   281.2 1834.65   294.1 1835.62   297.5 1837.66
   300.7 1840.65   304.0 1841.80   307.2 1842.19   317.0 1845.75   349.6 1853.67
   362.6 1858.15   417.7 1883.60   433.8 1893.10   440.3 1896.19   479.0 1909.40
#Mann= 3 , 0 , 0
       0     0.1       0   279.1   0.045       0   294.1     0.1       0
Bank Sta=279.1,294.1
Exp/Cntr=0.3,0.1

Type RM Length L Ch R = 1 ,23739.7,481.5,476.9,471.9
XS GIS Cut Line= 2
     2041923.135      255840.579     2041433.552      255723.391
#Sta/Elev= 30
       0 1924.78    49.0 1897.21    71.9 1885.18   111.1 1867.45   147.1 1852.40
   153.6 1847.37   166.7 1833.76   173.2 1828.68   178.6 1826.34   186.3 1825.54
   193.6 1827.09   209.2 1830.32   215.8 1832.43   222.3 1833.25   245.2 1832.24
   268.0 1834.74   284.4 1835.00   294.2 1834.14   300.7 1835.36   317.1 1834.04
   340.0 1834.95   353.0 1834.24   395.5 1837.88   428.2 1839.30   454.4 1844.22
   467.5 1848.52   487.1 1856.62   490.3 1858.88   500.1 1869.54   503.4 1871.83
#Mann= 3 , 0 , 0
       0     0.1       0   178.6   0.045       0   193.6     0.1       0
Bank Sta=178.6,193.6
Exp/Cntr=0.3,0.1

Type RM Length L Ch R = 1 ,23262.7,399.7,401.1,401.6
XS GIS Cut Line= 3
     2041958.292      255460.370     2041734.333      255340.579
     2041414.021      255332.766
#Sta/Elev= 30
       0 1866.26    26.0 1856.28    48.8 1849.36   104.2 1837.88   195.4 1830.17
   241.0 1825.05   263.8 1820.08   276.9 1819.94   286.7 1818.28   302.9 1817.49
   312.8 1816.46   317.9 1816.97   325.9 1821.74   329.2 1822.47   342.3 1819.45
   358.6  1819.8   368.4 1821.35   391.3 1816.68   404.4 1816.21   410.9 1816.69
   417.5 1819.38   427.3 1828.91   456.7 1851.95   509.0 1884.98   515.5 1887.34
   525.4 1889.16   531.9 1894.40   545.0 1902.34   554.8 1906.39   574.4 1917.19
#Mann= 3 , 0 , 0
       0     0.1       0   302.9   0.045       0   317.9     0.1       0
Bank Sta=302.9,317.9
Exp/Cntr=0.3,0.1

Type RM Length L Ch R = 1 ,22861.6,397.7,411.6,425.7
XS GIS Cut Line= 3
     2042054.646      255127.037     2041829.385      254961.672
     2041505.167      254946.047
#Sta/Elev= 30
       0 1875.07    32.5 1853.55    61.7 1836.28    91.0 1821.06   100.7 1818.00
   126.7 1816.74   165.7 1813.56   208.0 1812.15   227.4 1812.81   256.7 1811.36
   299.1 1812.76   312.2 1811.87   322.1 1808.44   345.0 1809.56   377.8 1805.34
   380.1 1805.34   387.6 1806.69   395.1 1810.00   410.6 1811.20   420.4 1814.95
   436.8 1817.69   440.1 1818.91   449.9 1824.66   466.3 1830.88   505.7 1842.85
   522.1 1848.92   538.5 1856.45   568.0 1872.68   587.6 1884.76   604.0 1892.68
#Mann= 3 , 0 , 0
       0     0.1       0   380.1   0.045       0   395.1     0.1       0
Bank Sta=380.1,395.1
Exp/Cntr=0.3,0.1

Type RM Length L Ch R = 1 ,22450,303.1,303.3,303.1
XS GIS Cut Line= 3
     2042193.969      254830.162     2041846.313      254551.516
     2041661.417      254545.006
#Sta/Elev= 30
       0 1845.23    13.1 1841.61    32.8 1834.60    85.2 1811.85   104.8 1806.29
   124.5 1805.69   137.6 1803.91   154.0 1803.55   176.9 1801.32   229.3 1801.94
   258.8 1800.20   321.0 1802.65   327.6 1801.63   337.4 1798.73   357.1 1798.60
     365 1797.54   376.8 1795.72   380.0 1795.76   389.8 1796.21   393.1 1797.35
   403.0 1805.79   412.8 1809.54   504.0 1812.72   523.4 1811.34   536.4 1813.51
   568.9 1817.04   585.1 1820.17   601.3 1820.80   614.3 1825.01   630.6 1829.03
#Mann= 3 , 0 , 0
       0     0.1       0     365   0.045       0     380     0.1       0
Bank Sta=365,380
Exp/Cntr=0.3,0.1

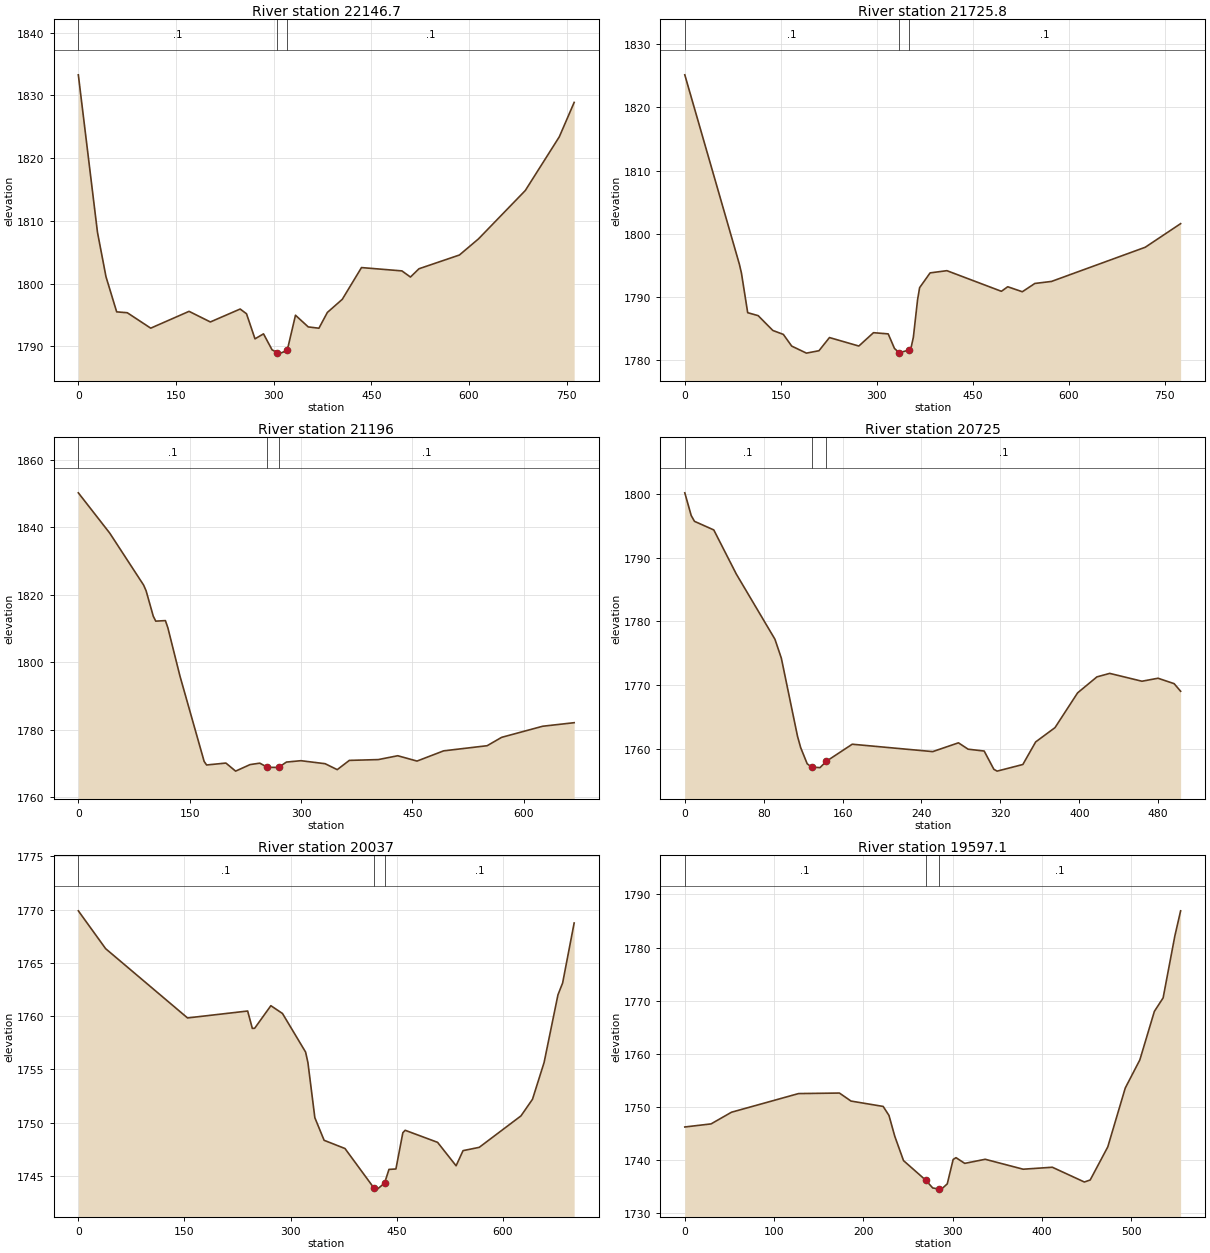
Type RM Length L Ch R = 1 ,22146.7,420.5,420.9,421.8
XS GIS Cut Line= 3
     2042385.375      254607.506     2041955.688      254259.850
     2041747.354      254242.922
#Sta/Elev= 30
       0 1833.29    29.4 1808.19    42.5 1801.10    58.9 1795.50    75.2 1795.36
   111.2 1792.90   170.1 1795.58   202.8 1793.89   248.6 1795.95   258.4 1795.19
   271.4  1791.2   284.5 1791.99   297.6 1789.45   305.9 1788.98   310.7 1788.92
   320.9 1789.35   333.6 1794.96   353.2 1793.10   369.6 1792.89   382.6 1795.41
   405.5 1797.50   435.0 1802.56   497.1 1802.03   510.2 1801.05   523.3 1802.37
   585.4 1804.56   614.8 1807.14   686.6 1814.84   738.9 1823.41   761.7 1828.89
#Mann= 3 , 0 , 0
       0     0.1       0   305.9   0.045       0   320.9     0.1       0
Bank Sta=305.9,320.9
Exp/Cntr=0.3,0.1

Type RM Length L Ch R = 1 ,21725.8,530.2,529.8,528.4
XS GIS Cut Line= 3
     2042664.021      254310.631     2042272.094      253977.297
     2042011.677      253977.297
#Sta/Elev= 30
       0 1825.13    85.2 1795.24    88.5 1793.82    98.3 1787.54   114.7 1787.07
   137.6 1784.73   154.0 1784.11   167.1 1782.26   190.1 1781.15   209.7 1781.53
   226.1 1783.61   272.0 1782.27   294.9 1784.38   317.9 1784.19   327.7 1781.89
     335 1781.22     350 1781.62   353.9 1782.14   357.2 1783.64   363.8 1789.60
   367.0 1791.50   383.4 1793.83   409.6 1794.18   494.8 1790.92   504.7 1791.64
   527.5 1790.85   547.1 1792.16   573.1 1792.48   719.6 1797.88   774.9 1801.61
#Mann= 3 , 0 , 0
       0     0.1       0     335   0.045       0     350     0.1       0
Bank Sta=335,350
Exp/Cntr=0.3,0.1

Type RM Length L Ch R = 1 ,21196,472.8,471.1,467.7
XS GIS Cut Line= 3
     2043033.813      253991.620     2042639.281      253697.350
     2042463.500      253697.350
#Sta/Elev= 30
       0 1850.22    42.4 1838.26    88.0 1822.87    91.3 1821.20   101.0 1813.64
   104.3 1812.20   117.3 1812.36   120.6 1810.26   136.9 1795.94   169.5 1770.64
   172.8 1769.58   198.8 1770.15   211.9 1767.76   231.4 1769.70   244.5 1770.12
   254.8 1768.89   269.8 1768.85   280.3 1770.44   299.9 1770.85   332.5 1769.96
   348.8 1768.20   365.1 1770.94   404.2 1771.18   430.3 1772.32   456.3 1770.74
   492.2 1773.77   550.8 1775.29   570.3 1777.77   625.6 1781.06   668.0 1782.11
#Mann= 3 , 0 , 0
       0     0.1       0   254.8   0.045       0   269.8     0.1       0
Bank Sta=254.8,269.8
Exp/Cntr=0.3,0.1

Type RM Length L Ch R = 1 ,20725,679,687.9,696.8
XS GIS Cut Line= 2
     2043201.781      253530.683     2042765.583      253280.683
#Sta/Elev= 30
       0 1800.15     6.5 1796.59     9.8 1795.68    29.4 1794.33    52.2 1787.42
    91.4 1777.19    97.9 1774.22   114.3 1761.97   117.5 1760.19   124.1 1757.66
   128.6 1757.12   137.1 1757.05   143.6 1758.05   169.8 1760.72   251.4 1759.56
   277.5 1760.94   287.3 1759.94   303.6 1759.65   313.4 1756.79   316.7 1756.50
   342.8 1757.54   355.8 1761.08   375.4 1763.32   398.3 1768.77   417.9 1771.28
   430.9 1771.83   463.6 1770.60   479.9 1771.07   496.2 1770.22   502.8 1769.03
#Mann= 3 , 0 , 0
       0     0.1       0   128.6   0.045       0   143.6     0.1       0
Bank Sta=128.6,143.6
Exp/Cntr=0.3,0.1

Type RM Length L Ch R = 1 ,20037,437.7,439.9,440.8
XS GIS Cut Line= 3
     2043346.313      253228.600     2043378.865      253071.047
     2043048.135      252643.964
#Sta/Elev= 30
       0 1769.88    38.6 1766.33   154.4 1759.83   239.4 1760.48   246.0 1758.85
   249.3 1758.86   272.2 1760.98   288.6 1760.25   321.3 1756.63   324.6 1755.64
   334.4 1750.47   347.5 1748.35   377.0 1747.58   417.9 1743.88   422.8 1743.77
   432.9 1744.33   439.2 1745.62   449.0 1745.66   458.8 1749.06   462.1 1749.29
   507.9 1748.16   534.1 1745.96   543.9 1747.38   566.8 1747.69   625.8 1750.64
   642.1 1752.20   658.5 1755.65   678.1 1762.00   684.7 1763.11   701.0 1768.74
#Mann= 3 , 0 , 0
       0     0.1       0   417.9   0.045       0   432.9     0.1       0
Bank Sta=417.9,432.9
Exp/Cntr=0.3,0.1

Type RM Length L Ch R = 1 ,19597.1,573,600.4,626.2
XS GIS Cut Line= 2
     2043727.823      252895.266     2043417.927      252434.329
#Sta/Elev= 30
       0 1746.22    29.4 1746.80    52.3 1749.00   127.4 1752.51   173.2 1752.61
   186.2 1751.10   222.2 1750.09   228.7 1748.40   235.2 1744.48   245.0 1739.89
   269.8 1736.22   277.7 1734.74   284.8 1734.54   287.5 1734.52   294.0 1735.51
   300.6 1740.10   303.8 1740.44   313.6 1739.37   336.5 1740.14   379.0 1738.27
   411.7 1738.64   447.6 1735.86   454.1 1736.24   473.8 1742.47   493.4 1753.56
   509.7 1758.85   526.0 1767.99   535.8 1770.53   548.9 1782.16   555.4 1786.92
#Mann= 3 , 0 , 0
       0     0.1       0   269.8   0.045       0   284.8     0.1       0
Bank Sta=269.8,284.8
Exp/Cntr=0.3,0.1

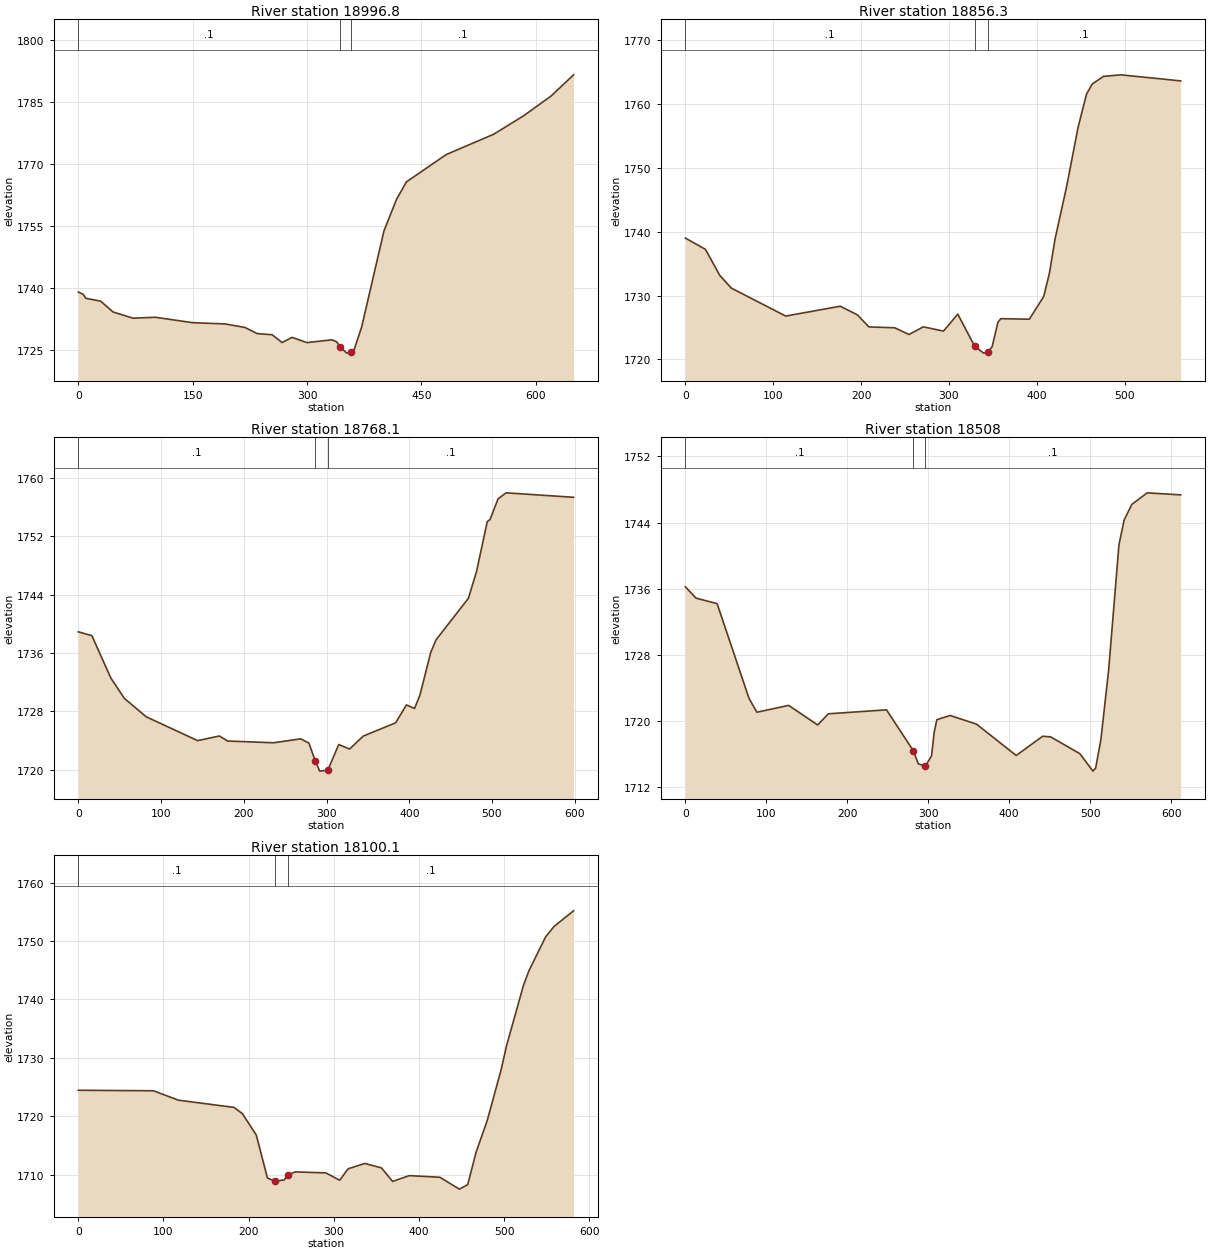
Type RM Length L Ch R = 1 ,18996.8,140.1,140.5,141
XS GIS Cut Line= 3
     2043858.730      252852.312     2044108.296      252470.368
     2044058.383      252283.736
#Sta/Elev= 30
       0 1738.96     6.5 1738.41     9.8 1737.46    29.3 1736.76    45.6 1734.14
    71.7 1732.64   101.0 1732.86   149.9 1731.55   192.3 1731.25   218.4 1730.40
   234.6 1728.90   254.2 1728.63   267.2 1726.75   280.3 1727.99   299.8 1726.73
   332.4 1727.40   338.9 1726.92   342.8 1725.77   352.0 1724.18   357.8 1724.40
   361.7 1725.03   371.5 1730.48   400.8 1753.76   417.1 1761.34   430.2 1765.62
   482.4 1772.24   544.7 1777.16   584.0 1781.64   620.0 1786.42   649.4 1791.54
#Mann= 3 , 0 , 0
       0     0.1       0   342.8   0.045       0   357.8     0.1       0
Bank Sta=342.8,357.8
Exp/Cntr=0.3,0.1

Type RM Length L Ch R = 1 ,18856.3,89.2,88.1,86.6
XS GIS Cut Line= 3
     2043973.758      252915.767     2044190.771      252601.531
     2044334.869      252490.420
#Sta/Elev= 30
       0 1739.01    22.8 1737.25    39.2 1733.16    52.2 1731.18   114.2 1726.79
   176.3 1728.33   195.8 1726.98   208.9 1725.09   238.3 1724.95   254.6 1723.90
   270.9 1725.10   293.8 1724.43   310.1 1727.09   329.3 1722.06   339.5 1720.98
   344.3 1721.18   349.2 1721.98   355.8 1725.82   359.0 1726.38   391.6 1726.30
   407.9 1729.86   414.4 1733.50   420.9 1738.91   433.9 1747.02   446.9 1756.28
   456.6 1761.56   463.1 1763.16   476.1 1764.36   495.6 1764.60   563.8 1763.65
#Mann= 3 , 0 , 0
       0     0.1       0   329.3   0.045       0   344.3     0.1       0
Bank Sta=329.3,344.3
Exp/Cntr=0.3,0.1

Type RM Length L Ch R = 1 ,18768.1,258.8,260.1,261.6
XS GIS Cut Line= 3
     2044058.827      252959.170     2044258.480      252643.197
     2044452.924      252530.350
#Sta/Elev= 30
       0 1738.90    16.4 1738.38    39.3 1732.58    55.7 1729.79    82.0 1727.28
   144.3 1724.01   170.5 1724.65   180.3 1723.96   236.1 1723.72   268.8 1724.26
   278.7 1723.67   286.5 1721.23   291.8 1719.84   301.5 1719.96   314.8 1723.48
   327.9 1722.86   344.3 1724.63   383.5 1726.45   396.6 1728.90   406.4 1728.42
   412.9 1730.23   425.9 1736.06   432.4 1737.81   471.5 1743.49   481.3 1747.14
   494.3 1753.99   497.6 1754.25   507.4 1757.11   517.1 1757.92   598.6 1757.31
#Mann= 3 , 0 , 0
       0     0.1       0   286.5   0.045       0   301.5     0.1       0
Bank Sta=286.5,301.5
Exp/Cntr=0.3,0.1

Type RM Length L Ch R = 1 ,18508,418.4,407.9,396.6
XS GIS Cut Line= 3
     2044269.490      253086.672     2044563.760      252662.193
     2044568.969      252567.141
#Sta/Elev= 30
       0 1736.23    13.1 1734.86    39.2 1734.19    78.5 1722.76    88.3 1721.06
   127.5 1721.89   163.4 1719.52   176.5 1720.87   248.4 1721.35   281.5 1716.41
   287.7 1714.81   296.5 1714.56   304.0 1715.78   307.3 1718.63   310.6 1720.16
   326.9 1720.67   359.6 1719.62   408.6 1715.83   441.3 1718.16   451.1 1718.08
   487.1 1716.06   503.4 1713.94   506.7 1714.31   513.2 1717.74   522.8 1726.20
   535.5 1741.31   541.9 1744.30   551.4 1746.19   570.4 1747.59   611.7 1747.34
#Mann= 3 , 0 , 0
       0     0.1       0   281.5   0.045       0   296.5     0.1       0
Bank Sta=281.5,296.5
Exp/Cntr=0.3,0.1

Type RM Length L Ch R = 1 ,18100.1,338.1,323.2,306.5
XS GIS Cut Line= 3
     2044764.281      253265.058     2044821.573      252801.516
     2044804.646      252688.235
#Sta/Elev= 30
       0 1724.43    88.2 1724.34   117.6 1722.73   182.9 1721.49   192.7 1720.42
   209.0 1716.77   222.1 1709.40   230.8 1708.86   241.7 1709.07   245.8 1709.90
   254.8 1710.45   290.7 1710.28   307.0 1709.02   316.8 1710.98   336.4 1711.89
   356.0 1711.14   369.1 1708.82   388.7 1709.81   424.6 1709.53   447.5 1707.50
   457.3 1708.27   467.1 1713.80   480.2 1719.24   496.5 1727.92   503.1 1732.16
   522.7 1742.36   529.2 1744.89   548.9 1750.72   558.7 1752.48   581.6 1755.15
#Mann= 3 , 0 , 0
       0     0.1       0   230.8   0.045       0   245.8     0.1       0
Bank Sta=230.8,245.8
Exp/Cntr=0.3,0.1