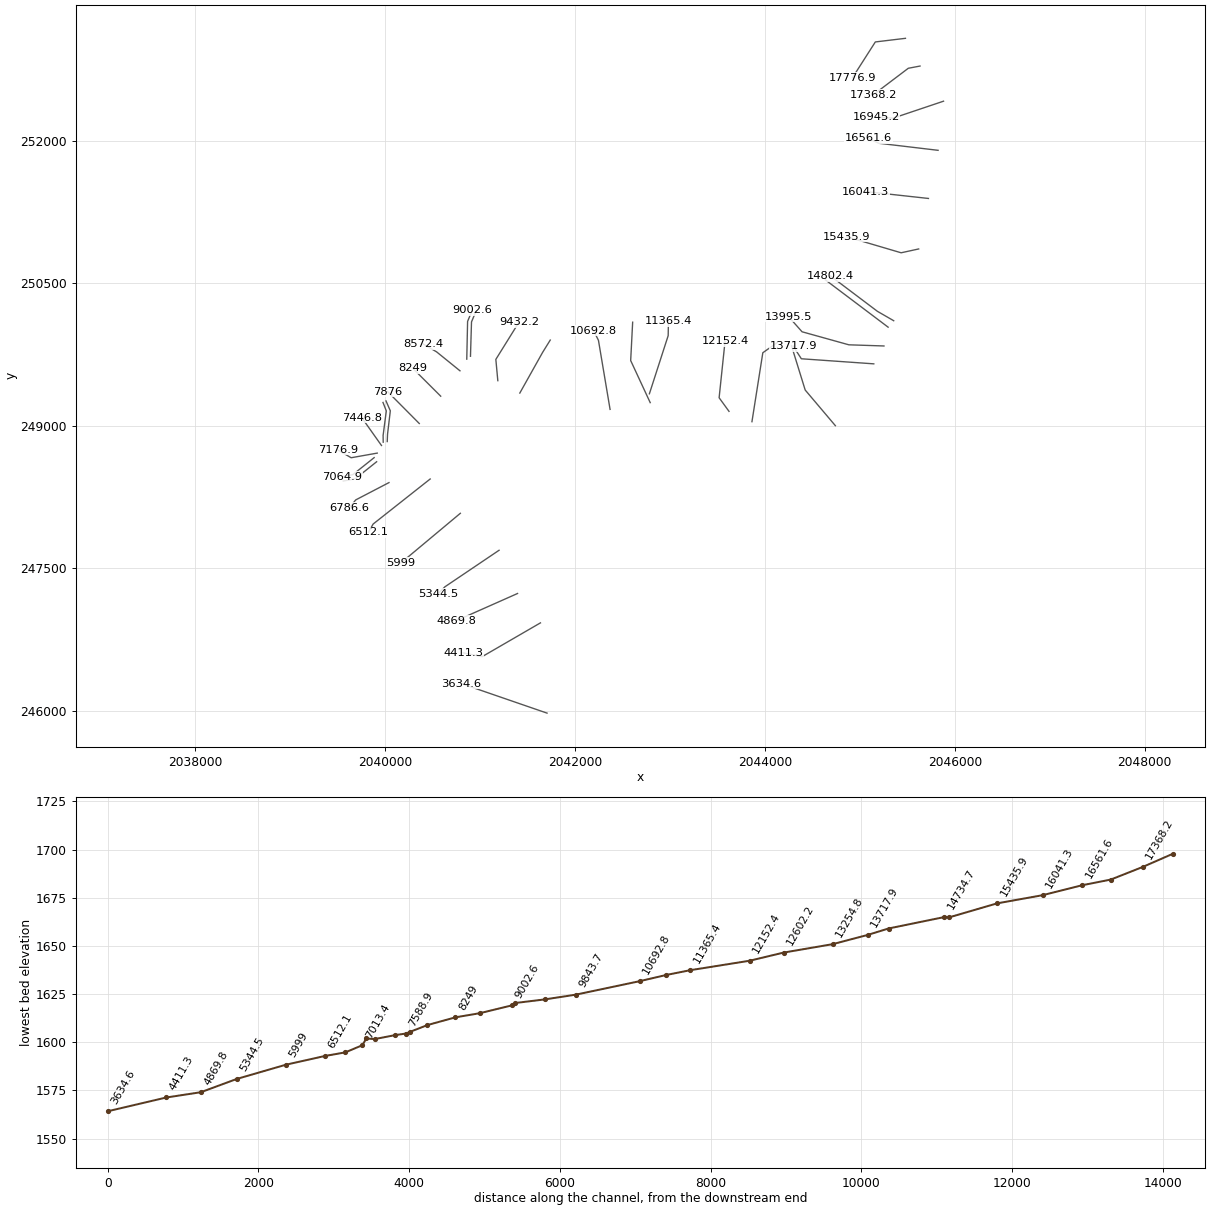
HEC-RAS study HNGRDCK.prj: HNGRDCK

--- HNGRDCK.g01 (geometry) --- (continued)

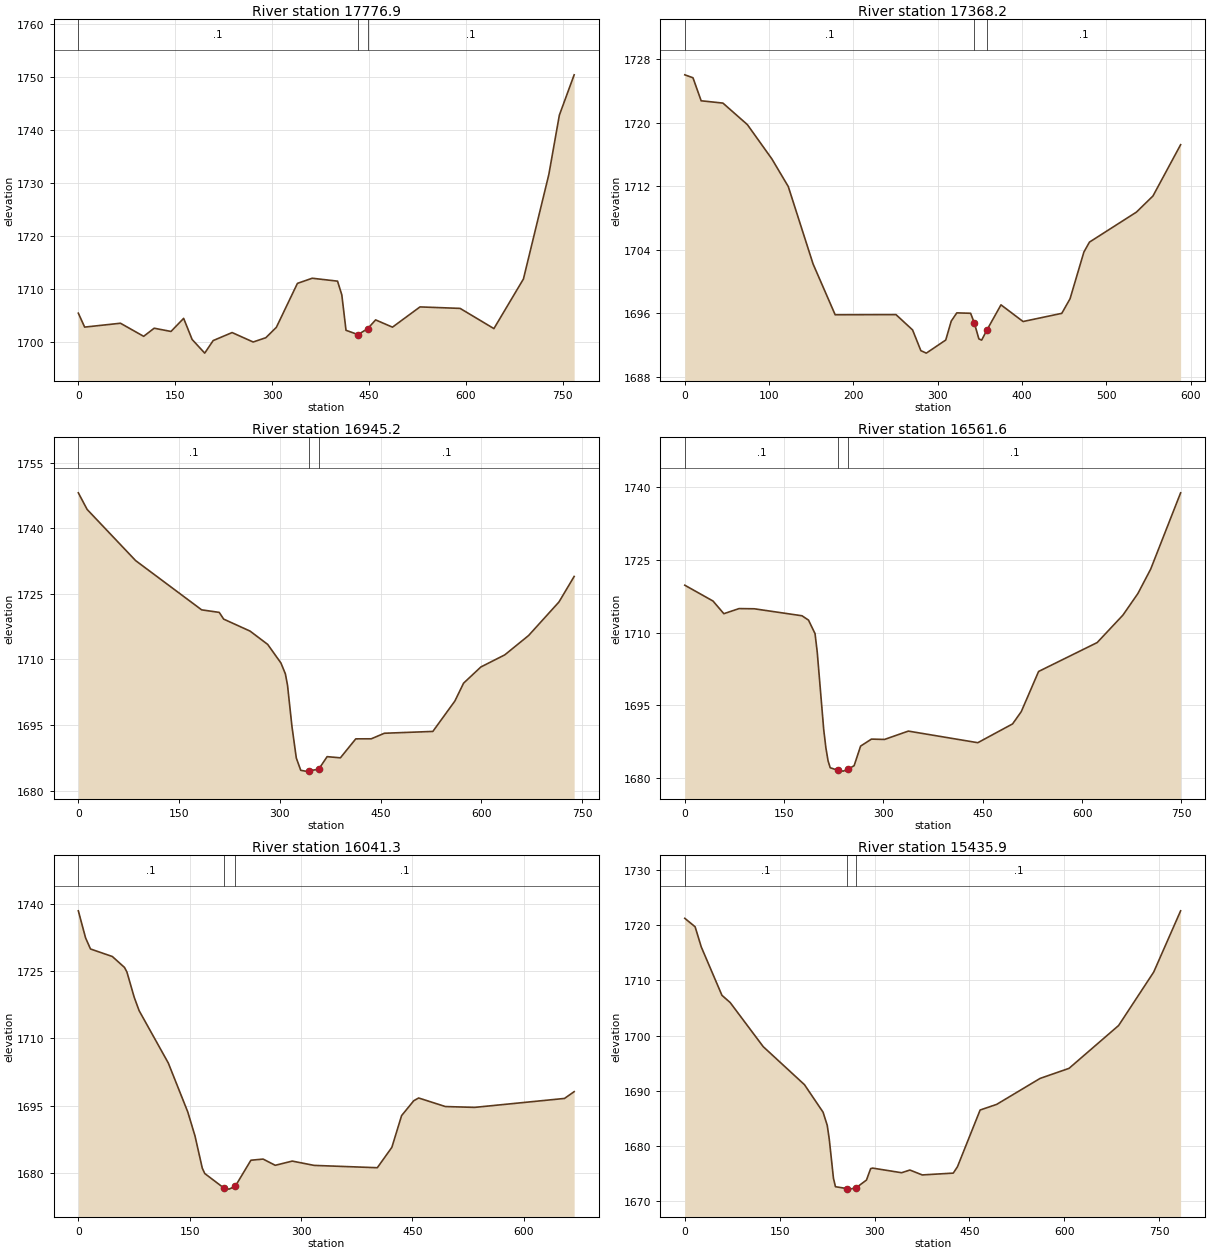
Type RM Length L Ch R = 1 ,17776.9,417.3,408.7,399.9
XS GIS Cut Line= 3
     2045480.427      253076.256     2045163.191      253038.193
     2044921.833      252660.891
#Sta/Elev= 30
       0 1705.50     9.8 1702.87    65.2 1703.60   101.1 1701.13   117.4 1702.66
   143.4 1702.05   163.0 1704.52   176.1 1700.54   195.6 1697.96   208.7 1700.33
   238.0 1701.84   270.6 1700.06   290.2 1700.87   306.5 1702.83   339.1 1711.12
   362.0 1712.09   401.2 1711.54   407.8 1708.95   414.3 1702.27   432.7 1701.46
   447.7 1702.55   460.1 1704.23   486.2 1702.86   528.8 1706.68   590.9 1706.40
   643.2 1702.59   688.9 1711.95   728.2 1731.66   744.5 1742.86   767.4 1750.47
#Mann= 3 , 0 , 0
       0     0.1       0   432.7   0.045       0   447.7     0.1       0
Bank Sta=432.7,447.7
Exp/Cntr=0.3,0.1

Type RM Length L Ch R = 1 ,17368.2,429.4,423.1,415.1
XS GIS Cut Line= 3
     2045634.073      252784.589     2045510.375      252761.152
     2045141.885      252482.506
#Sta/Elev= 30
       0 1726.02     9.7 1725.65    19.4 1722.75    45.2 1722.46    74.2 1719.75
   103.3 1715.42   122.7 1711.95   152.1 1702.20   178.3 1695.80   250.4 1695.82
   270.1 1693.89   279.9 1691.28   286.4 1690.97   309.4 1692.62   315.9 1695.00
   322.5 1696.04   338.9 1695.99   343.2 1694.80   348.7 1692.76   352.0 1692.61
   358.2 1693.88   374.9 1697.05   401.1 1694.95   447.0 1695.98   456.8 1697.82
   473.2 1703.70   479.8 1704.95   535.5 1708.73   555.1 1710.76   587.9 1717.22
#Mann= 3 , 0 , 0
       0     0.1       0   343.2   0.045       0   358.2     0.1       0
Bank Sta=343.2,358.2
Exp/Cntr=0.3,0.1

Type RM Length L Ch R = 1 ,16945.2,393.6,383.6,373.6
XS GIS Cut Line= 3
     2045881.469      252414.797     2045350.219      252236.412
     2045173.135      252248.131
#Sta/Elev= 30
       0 1748.08    13.1 1744.28    85.2 1732.59   183.5 1721.32   209.7 1720.74
   216.3 1719.20   255.6 1716.46   281.8 1713.42   301.5 1709.17   308.1 1706.70
   311.3 1704.11   317.9 1694.68   324.4 1687.44   331.0 1684.63   337.6 1684.44
   342.8 1684.46   357.8 1684.90   370.3 1687.75   390.0 1687.48   412.9 1691.82
   435.9 1691.83   455.5 1693.10   527.6 1693.52   560.4 1700.47   573.3 1704.55
   599.1 1708.26   634.6 1711.02   670.1 1715.45   715.3 1723.12   737.9 1728.96
#Mann= 3 , 0 , 0
       0     0.1       0   342.8   0.045       0   357.8     0.1       0
Bank Sta=342.8,357.8
Exp/Cntr=0.3,0.1

Type RM Length L Ch R = 1 ,16561.6,520.2,520.3,520.5
XS GIS Cut Line= 3
     2045824.177      251897.870     2045199.177      251972.089
     2045091.104      252022.870
#Sta/Elev= 30
       0 1719.78    42.6 1716.52    59.0 1713.91    82.0 1714.96   104.9 1714.92
   177.0 1713.48   186.8 1712.59   196.7 1709.80   200.0 1706.01   209.8 1690.01
   213.1 1686.24   216.4 1683.57   219.6 1682.16   231.6 1681.61   239.3 1681.46
   246.6 1681.87   255.7 1682.58   265.5 1686.62   281.9 1688.06   301.6 1687.99
   337.6 1689.71   442.5 1687.32   495.0 1691.19   508.1 1693.71   534.3 1702.00
   622.8 1707.96   661.7 1713.62   684.2 1718.05   703.6 1723.10   748.8 1738.82
#Mann= 3 , 0 , 0
       0     0.1       0   231.6   0.045       0   246.6     0.1       0
Bank Sta=231.6,246.6
Exp/Cntr=0.3,0.1

Type RM Length L Ch R = 1 ,16041.3,609.3,605.3,601.3
XS GIS Cut Line= 2
     2045722.615      251391.360     2045058.552      251464.277
#Sta/Elev= 30
       0 1738.48     9.8 1732.42    16.4 1729.96    45.8 1728.28    62.2 1725.84
    65.5 1724.80    75.3 1719.17    81.9 1716.19   121.2 1704.50   147.4 1693.60
   157.2 1688.20   167.0 1681.02   170.3 1679.83   196.4 1676.55   203.0 1676.34
   211.4 1676.97   232.5 1682.79   248.9 1683.05   265.3 1681.66   288.2 1682.60
   317.6 1681.64   402.8 1681.12   422.4 1685.67   435.5 1692.75   451.9 1696.08
   458.5 1696.69   494.5 1694.78   533.8 1694.59   655.0 1696.59   668.0 1698.10
#Mann= 3 , 0 , 0
       0     0.1       0   196.4   0.045       0   211.4     0.1       0
Bank Sta=196.4,211.4
Exp/Cntr=0.3,0.1

Type RM Length L Ch R = 1 ,15435.9,640.8,633.5,624.9
XS GIS Cut Line= 3
     2045619.750      250860.110     2045434.854      250819.745
     2044864.542      250987.714
#Sta/Elev= 30
       0 1721.30    16.3 1719.76    26.1 1716.08    58.7 1707.31    71.8 1705.98
   124.0 1697.97   189.2 1691.06   218.6 1686.06   225.2 1683.66   228.4 1681.13
   235.0 1674.05   238.2 1672.52   255.9 1672.19   261.1 1672.08   270.9 1672.33
   287.2 1673.73   293.8 1675.81   297.0 1675.90   342.8 1675.06   355.8 1675.55
   375.4 1674.66   424.4 1674.99   431.0 1676.14   466.9 1686.46   493.0 1687.48
   561.6 1692.20   607.4 1694.03   685.8 1701.82   741.3 1711.54   783.8 1722.66
#Mann= 3 , 0 , 0
       0     0.1       0   255.9   0.045       0   270.9     0.1       0
Bank Sta=255.9,270.9
Exp/Cntr=0.3,0.1

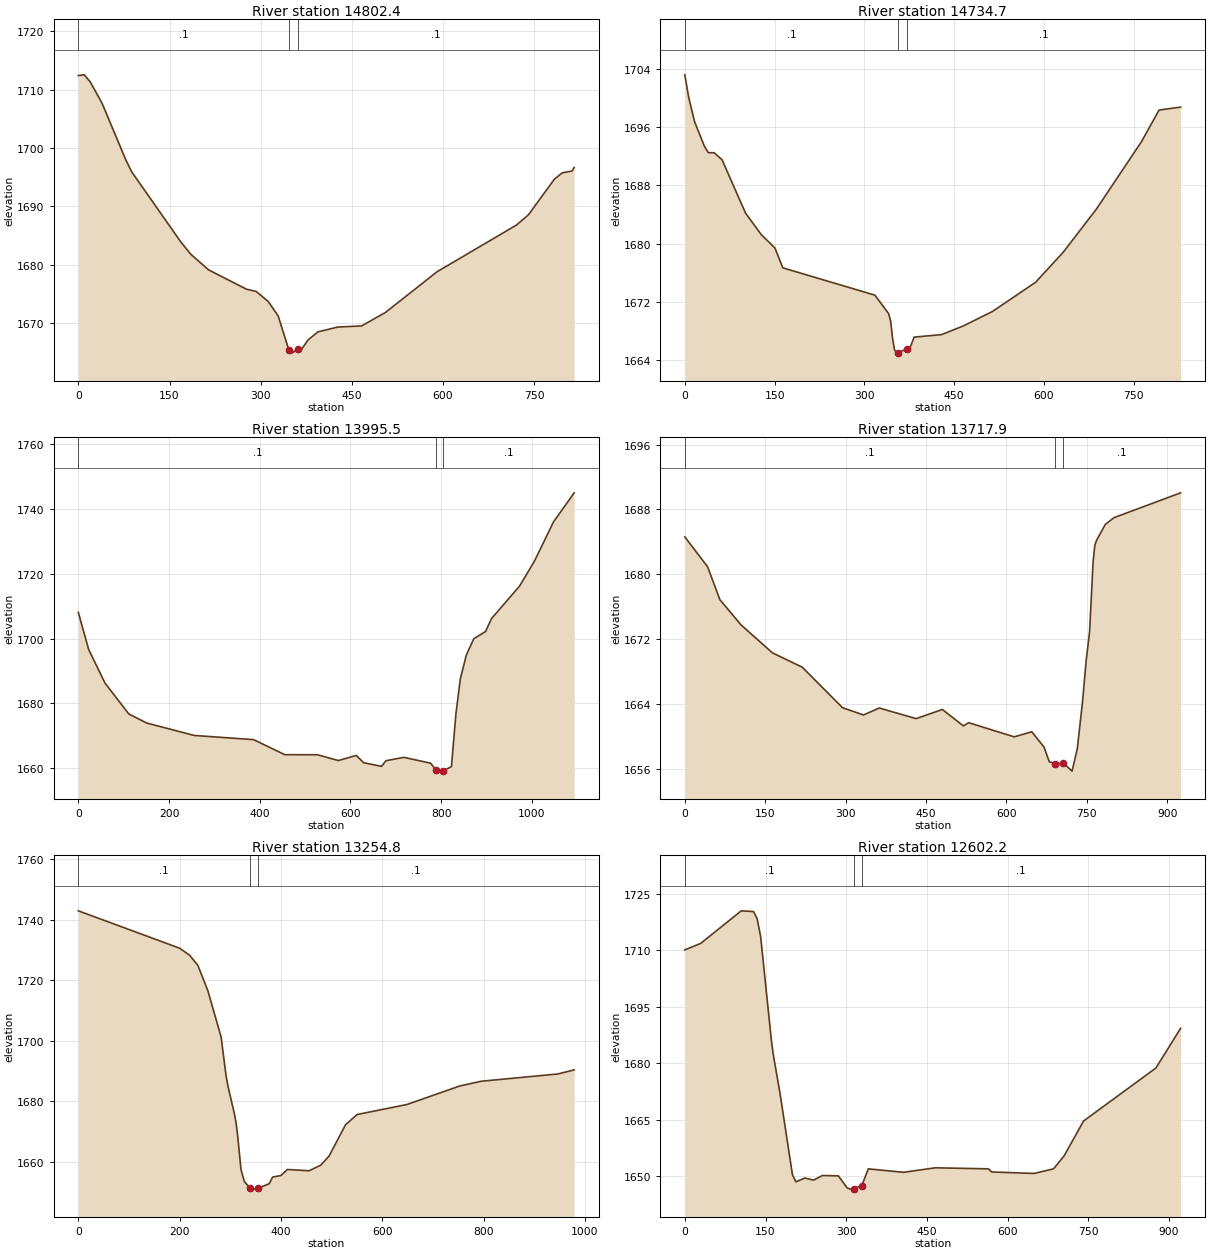
Type RM Length L Ch R = 1 ,14802.4,67.8,67.7,67.6
XS GIS Cut Line= 3
     2045356.729      250104.902     2045185.184      250203.730
     2044691.799      250575.388
#Sta/Elev= 30
       0 1712.43     9.7 1712.55    19.5 1711.35    39.0 1707.69    77.9 1698.03
    87.6 1695.95   168.8 1683.88   185.0 1681.80   214.3 1679.12   276.4 1675.82
   292.8 1675.41   312.4 1673.70   328.7 1671.25   346.5 1665.35   348.3 1664.89
   351.6 1664.85   361.5 1665.63   367.9 1665.58   377.7 1667.09   394.1 1668.49
   426.8 1669.32   466.0 1669.51   505.2 1671.82   590.2 1678.80   720.9 1686.81
   740.5 1688.56   783.0 1694.64   796.1 1695.75   812.4 1696.07   815.7 1696.65
#Mann= 3 , 0 , 0
       0     0.1       0   346.5   0.045       0   361.5     0.1       0
Bank Sta=346.5,361.5
Exp/Cntr=0.3,0.1

Type RM Length L Ch R = 1 ,14734.7,730.5,739.2,747.2
XS GIS Cut Line= 2
     2045297.701      250037.193     2044636.243      250535.457
#Sta/Elev= 30
       0 1703.18     6.6 1700.05    16.4 1696.73    32.7 1693.38    39.3 1692.49
    49.1 1692.48    62.2 1691.52   101.5 1684.19   127.7 1681.24   150.6 1679.40
   163.7 1676.68   317.5 1672.93   340.4 1670.40   343.7 1669.40   347.0 1667.01
   350.2 1665.45   353.5 1664.97   356.4 1665.05   371.4 1665.58   376.4 1665.76
   383.0 1667.17   428.8 1667.51   464.8 1668.69   513.9 1670.69   585.9 1674.70
   631.7 1678.79   687.4 1684.74   762.7 1694.00   792.1 1698.34   828.1 1698.75
#Mann= 3 , 0 , 0
       0     0.1       0   356.4   0.045       0   371.4     0.1       0
Bank Sta=356.4,371.4
Exp/Cntr=0.3,0.1

Type RM Length L Ch R = 1 ,13995.5,272.6,277.6,282.4
XS GIS Cut Line= 4
     2045254.299      249839.277     2044884.507      249851.429
     2044391.451      249988.582     2044250.826      250146.568
#Sta/Elev= 30
       0 1708.09    22.9 1696.60    58.9 1686.23   111.3 1676.71   150.6 1673.91
   255.4 1670.07   386.4 1668.77   455.3 1664.12   527.5 1664.10   573.4 1662.31
   612.8 1663.89   629.2 1661.64   668.5 1660.51   678.4 1662.26   717.7 1663.30
   776.8 1661.50   789.5 1659.24   796.5 1659.04   804.5 1659.13   822.7 1660.43
   832.6 1676.75   842.4 1687.62   855.5 1694.89   871.9 1699.94   898.0 1702.19
   911.0 1706.17   972.9 1716.21  1005.4 1723.84  1047.7 1736.03  1093.3 1745.04
#Mann= 3 , 0 , 0
       0     0.1       0   789.5   0.045       0   804.5     0.1       0
Bank Sta=789.5,804.5
Exp/Cntr=0.3,0.1

Type RM Length L Ch R = 1 ,13717.9,481.5,463.1,444.4
XS GIS Cut Line= 3
     2045147.033      249651.212     2044384.012      249704.598
     2044296.773      249838.712
#Sta/Elev= 30
       0 1684.60    42.5 1680.92    65.4 1676.86   104.6 1673.76   163.4 1670.29
   219.0 1668.52   294.2 1663.52   333.4 1662.62   362.8 1663.48   431.5 1662.17
   480.5 1663.30   519.7 1661.27   529.5 1661.67   614.5 1659.92   647.2 1660.55
   670.1 1658.66   679.9 1656.84   691.4 1656.62   706.4 1656.66   722.4 1655.69
   732.2 1658.48   742.0 1664.29   748.5 1669.19   755.1 1672.92   761.6 1681.49
   764.9 1683.58   768.2 1684.19   784.5 1686.15   800.8 1686.98   924.9 1690.04
#Mann= 3 , 0 , 0
       0     0.1       0   691.4   0.045       0   706.4     0.1       0
Bank Sta=691.4,706.4
Exp/Cntr=0.3,0.1

Type RM Length L Ch R = 1 ,13254.8,671.5,652.6,632.8
XS GIS Cut Line= 3
     2044742.146      249000.735     2044424.438      249375.735
     2044280.340      249841.013
#Sta/Elev= 30
       0 1742.95   199.9 1730.59   219.5 1728.30   235.9 1724.93   255.6 1716.57
   281.8 1701.23   291.6 1688.38   294.9 1685.33   308.0 1675.83   311.3 1672.87
   314.6 1668.39   321.1 1657.31   327.7 1653.45   339.1 1651.23   347.3 1650.92
   354.1 1651.13   376.8 1652.72   383.4 1654.90   399.8 1655.42   412.8 1657.42
   455.4 1656.99   478.4 1658.85   494.8 1661.83   527.4 1672.22   550.3 1675.59
   648.4 1678.90   753.0 1685.03   795.5 1686.60   945.9 1688.99   978.6 1690.34
#Mann= 3 , 0 , 0
       0     0.1       0   339.1   0.045       0   354.1     0.1       0
Bank Sta=339.1,354.1
Exp/Cntr=0.3,0.1

Type RM Length L Ch R = 1 ,12602.2,450.1,449.8,449
XS GIS Cut Line= 3
     2043863.674      249042.402     2043978.257      249768.096
     2044131.035      249875.735
#Sta/Elev= 30
       0 1710.16    29.5 1711.88   105.0 1720.55   127.9 1720.35   134.5 1718.42
   141.0 1713.68   160.7 1686.42   164.0 1682.70   177.1 1671.92   200.1 1650.34
   206.6 1648.47   223.0 1649.48   239.4 1648.93   255.8 1650.15   285.4 1650.06
   301.8 1646.84   308.3 1646.53     314 1646.68     329 1647.48   341.1 1651.92
   406.7 1651.01   465.7 1652.20   564.1 1651.93   570.7 1651.09   649.4 1650.70
   685.5 1651.93   705.2 1655.41   741.2 1664.65   875.7 1678.75   921.6 1689.31
#Mann= 3 , 0 , 0
       0     0.1       0     314   0.045       0     329     0.1       0
Bank Sta=314,329
Exp/Cntr=0.3,0.1

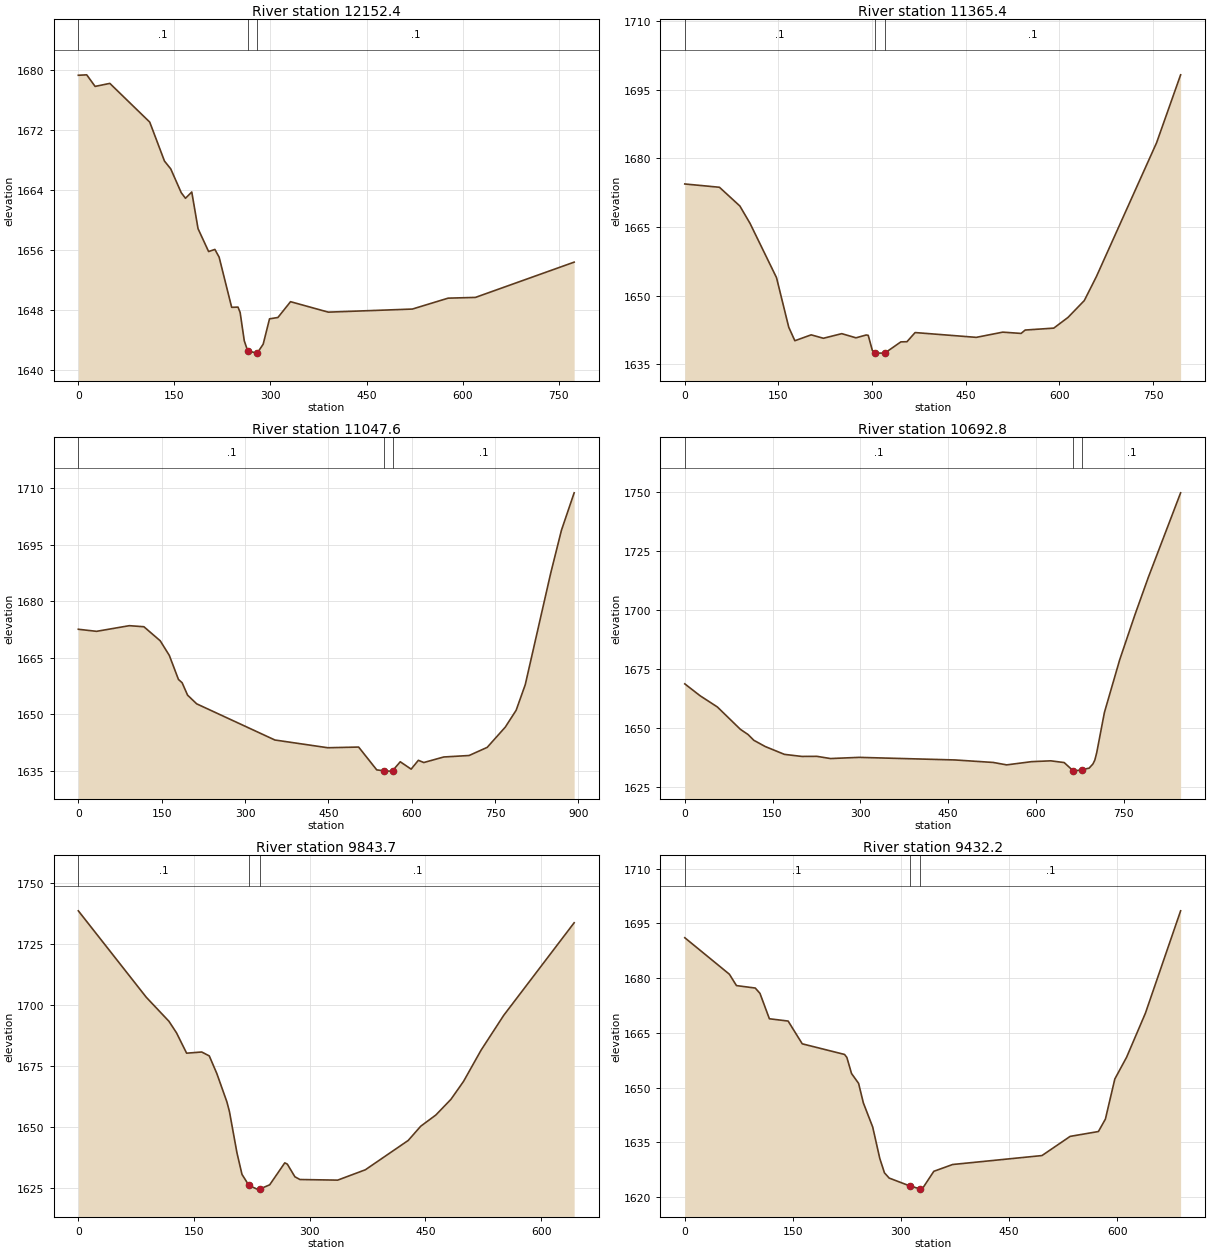
Type RM Length L Ch R = 1 ,12152.4,789.8,787,772.9
XS GIS Cut Line= 3
     2043622.065      249151.198     2043517.898      249294.427
     2043580.398      249888.177
#Sta/Elev= 30
       0 1679.26    13.1 1679.32    26.2 1677.78    49.2 1678.18   111.5 1673.03
   134.5 1667.85   144.3 1666.81   160.7 1663.64   167.3 1662.90   177.1 1663.74
   186.9 1658.86   203.4 1655.82   213.2 1656.10   219.8 1655.08   239.4 1648.40
   249.3 1648.43   252.6 1647.72   259.1 1643.94   264.4 1642.61   278.8 1642.31
   279.4 1642.33   288.6 1643.50   298.5 1646.87   311.6 1647.05   331.3 1649.15
   390.3 1647.76   521.5 1648.17   577.3 1649.62   620.0 1649.72   774.1 1654.41
#Mann= 3 , 0 , 0
       0     0.1       0   264.4   0.045       0   279.4     0.1       0
Bank Sta=264.4,279.4
Exp/Cntr=0.3,0.1

Type RM Length L Ch R = 1 ,11365.4,310.7,317.7,324.3
XS GIS Cut Line= 3
     2042783.523      249336.094     2042981.440      249948.073
     2042984.044      250099.115
#Sta/Elev= 30
       0 1674.42    55.5 1673.70    88.2 1669.60   104.5 1665.80   146.9 1653.93
   166.5 1643.08   176.3 1640.12   202.4 1641.41   222.0 1640.66   251.4 1641.67
   274.2 1640.76   290.6 1641.38   293.8 1641.30   300.4 1638.01   305.4 1637.43
   320.0 1637.41   320.4 1637.42   346.1 1639.87   355.9 1639.91   368.9 1641.91
   466.9 1640.86   509.3 1642.00   538.7 1641.72   545.2 1642.46   591.0 1642.88
   613.8 1645.22   639.9 1648.91   659.3 1654.16   755.7 1683.44   794.2 1698.30
#Mann= 3 , 0 , 0
       0     0.1       0   305.4   0.045       0   320.4     0.1       0
Bank Sta=305.4,320.4
Exp/Cntr=0.3,0.1

Type RM Length L Ch R = 1 ,11047.6,350.8,354.8,358.8
XS GIS Cut Line= 3
     2042792.215      249243.009     2042586.486      249685.718
     2042607.320      250089.363
#Sta/Elev= 30
       0 1672.55    32.8 1672.00    91.7 1673.50   118.0 1673.22   147.4 1669.49
   163.8 1665.61   180.2 1659.25   186.8 1658.37   196.6 1655.09   213.0 1652.78
   353.8 1643.19   448.9 1641.14   504.5 1641.32   537.1 1635.27   550.5 1635.02
   559.9 1634.94   565.5 1635.04   579.4 1637.42   599.0 1635.47   612.0 1637.81
   621.8 1637.22   657.7 1638.69   703.3 1639.08   735.9 1641.24   768.5 1646.62
   788.0 1651.08   804.4 1657.86   850.0 1687.30   869.5 1698.79   892.4 1708.72
#Mann= 3 , 0 , 0
       0     0.1       0   550.5   0.045       0   565.5     0.1       0
Bank Sta=550.5,565.5
Exp/Cntr=0.3,0.1

Type RM Length L Ch R = 1 ,10692.8,864.3,849.2,833.7
XS GIS Cut Line= 3
     2042369.461      249172.031     2042247.065      249898.594
     2042197.586      249997.552
#Sta/Elev= 30
       0 1668.73    26.2 1663.68    55.7 1658.92    95.0 1649.44   108.1 1647.24
   117.9 1644.80   137.5 1642.13   170.3 1638.81   199.8 1637.94   226.0 1637.97
   248.9 1637.04   298.0 1637.54   461.7 1636.44   527.2 1635.38   550.1 1634.35
   592.7 1635.72   625.5 1636.07   648.4 1635.33   664.1 1631.77   664.8 1631.70
   679.1 1632.32   691.0 1632.96   697.5 1634.72   700.8 1636.40   704.0 1639.53
   717.2 1656.64   743.3 1678.98   769.3 1698.04   792.1 1713.87   847.4 1749.80
#Mann= 3 , 0 , 0
       0     0.1       0   664.1   0.045       0   679.1     0.1       0
Bank Sta=664.1,679.1
Exp/Cntr=0.3,0.1

Type RM Length L Ch R = 1 ,9843.7,412.1,411.4,410
XS GIS Cut Line= 3
     2041418.940      249343.906     2041658.523      249770.990
     2041739.252      249901.198
#Sta/Elev= 30
       0 1738.51    88.1 1703.16   117.5 1693.33   127.3 1688.61   140.4 1680.29
   160.0 1680.77   169.8 1679.17   179.6 1671.95   192.6 1660.40   195.9 1656.47
   205.7 1639.51   212.2 1630.72   221.2 1626.20   231.8 1624.69   236.2 1624.85
   248.1 1626.45   267.7 1635.44   271.0 1634.90   280.8 1629.75   287.3 1628.62
   336.3 1628.37   372.2 1632.61   427.7 1644.59   444.0 1650.43   463.6 1655.01
   483.2 1661.44   499.5 1668.77   522.3 1681.57   551.6 1695.78   642.9 1733.63
#Mann= 3 , 0 , 0
       0     0.1       0   221.2   0.045       0   236.2     0.1       0
Bank Sta=221.2,236.2
Exp/Cntr=0.3,0.1

Type RM Length L Ch R = 1 ,9432.2,376.3,388.7,400.8
XS GIS Cut Line= 3
     2041187.169      249474.115     2041166.336      249698.073
     2041411.127      250091.302
#Sta/Elev= 30
       0 1691.05    61.9 1681.06    71.7 1677.95    97.8 1677.28   104.3 1675.83
   117.4 1668.87   143.4 1668.24   163.0 1662.01   221.7 1659.10   224.9 1658.29
   231.4 1653.88   241.2 1651.18   247.8 1645.84   260.8 1639.21   270.6 1630.63
   277.1 1626.69   283.6 1625.26   311.9 1623.13   326.9 1622.27   329.3 1622.23
   345.6 1627.11   371.7 1628.97   495.7 1631.42   534.8 1636.67   574.0 1638.00
   583.7 1641.40   596.8 1652.39   613.1 1658.33   639.2 1670.38   688.1 1698.42
#Mann= 3 , 0 , 0
       0     0.1       0   311.9   0.045       0   326.9     0.1       0
Bank Sta=311.9,326.9
Exp/Cntr=0.3,0.1

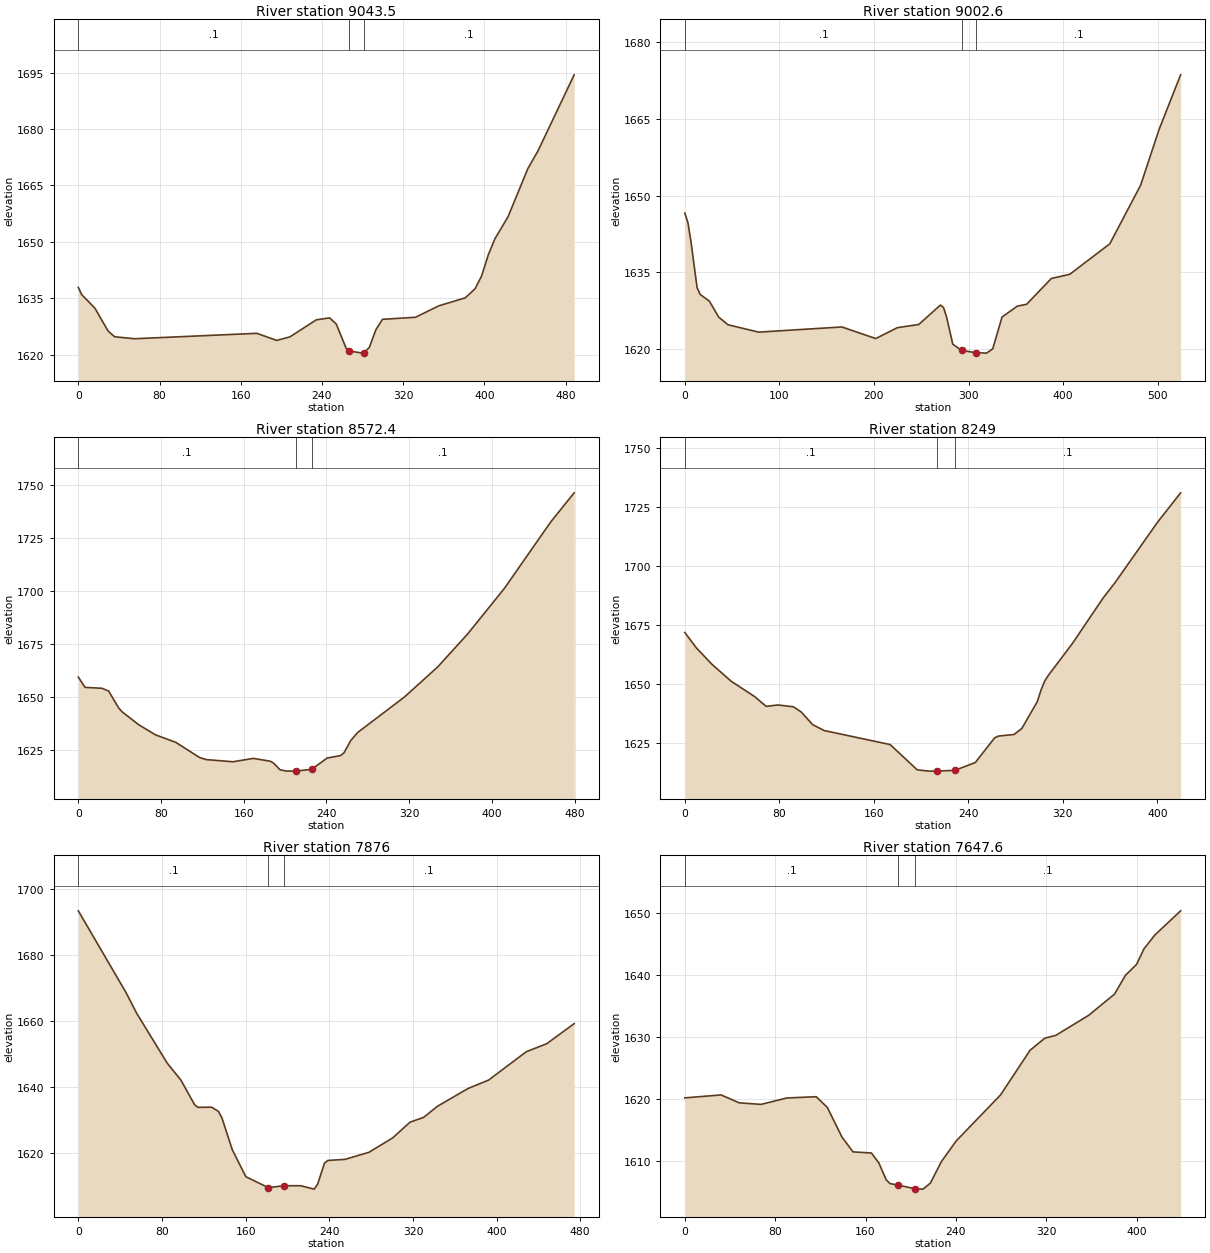
Type RM Length L Ch R = 1 ,9043.5,40.8,40.9,41.1
XS GIS Cut Line= 3
     2040899.192      249730.951     2040910.042      250092.279
     2040958.870      250209.466
#Sta/Elev= 30
       0 1637.86     3.3 1635.96    16.3 1632.36    29.3 1626.27    35.8 1624.73
    55.4 1624.21   175.9 1625.65   195.4 1623.76   208.4 1624.70   234.5 1629.25
   247.5 1629.76   254.0 1628.16   263.8 1621.69   266.3 1620.97   280.1 1620.38
   281.3 1620.48   286.6 1621.87   293.1 1626.61   299.6 1629.38   332.2 1629.93
   355.0 1632.96   381.0 1635.08   390.8 1637.50   397.3 1640.96   403.8 1646.52
   410.3 1650.79   423.3 1656.69   442.9 1669.55   452.6 1674.11   488.4 1694.45
#Mann= 3 , 0 , 0
       0     0.1       0   266.3   0.045       0   281.3     0.1       0
Bank Sta=266.3,281.3
Exp/Cntr=0.3,0.1

Type RM Length L Ch R = 1 ,9002.6,409.2,430.3,450.4
XS GIS Cut Line= 3
     2040860.129      249700.569     2040868.810      250097.704
     2040917.638      250214.892
#Sta/Elev= 30
       0 1646.60     3.3 1644.72     6.5 1641.06    13.0 1632.00    16.3 1630.68
    26.0 1629.36    35.8 1626.25    45.6 1624.75    78.1 1623.30   166.1 1624.31
   201.9 1622.04   224.7 1624.17   247.4 1624.80   270.2 1628.59   273.5 1628.13
   276.8 1626.25   283.3 1620.94   292.8 1619.71   307.8 1619.28   319.1 1619.19
   325.6 1620.04   335.4 1626.26   351.6 1628.39   361.4 1628.75   387.5 1633.80
   407.0 1634.62   449.3 1640.58   481.9 1652.05   501.4 1662.95   524.2 1673.66
#Mann= 3 , 0 , 0
       0     0.1       0   292.8   0.045       0   307.8     0.1       0
Bank Sta=292.8,307.8
Exp/Cntr=0.3,0.1

Type RM Length L Ch R = 1 ,8572.4,325.3,323.4,320.8
XS GIS Cut Line= 3
     2040788.515      249577.956     2040543.289      249776.523
     2040401.912      249859.857
#Sta/Elev= 30
       0 1659.37     6.5 1654.54    22.8 1654.11    29.3 1652.81    39.0 1644.85
    42.3 1643.04    58.6 1636.88    74.8 1632.14    94.3 1628.65   117.1 1621.54
   123.6 1620.53   149.6 1619.50   169.2 1621.09   185.4 1619.79   188.7 1618.94
   195.2 1615.70   201.7 1615.09   210.6 1615.14   225.6 1615.92   240.7 1621.25
   253.7 1622.44   257.0 1623.73   263.5 1629.50   270.0 1633.21   315.5 1650.02
   347.7 1664.20   376.7 1679.76   412.1 1701.14   457.1 1732.55   479.6 1746.16
#Mann= 3 , 0 , 0
       0     0.1       0   210.6   0.045       0   225.6     0.1       0
Bank Sta=210.6,225.6
Exp/Cntr=0.3,0.1

Type RM Length L Ch R = 1 ,8249,372.7,373,372.1
XS GIS Cut Line= 2
     2040585.607      249311.029     2040288.298      249607.253
#Sta/Elev= 30
       0 1671.77     9.8 1665.23    23.0 1658.26    39.4 1651.03    59.0 1644.62
    68.9 1640.41    78.7 1641.01    91.8 1640.26    98.4 1638.11   108.2 1632.67
   118.0 1630.16   173.8 1624.21   196.7 1613.50   206.6 1612.94   213.6 1612.96
   228.6 1613.26   245.9 1616.59   262.3 1627.08   265.6 1627.82   278.7 1628.48
   285.3 1631.05   298.4 1642.44   301.6 1647.45   304.9 1651.40   308.2 1653.90
   327.9 1666.95   354.1 1686.40   364.0 1692.80   400.0 1718.44   419.7 1731.03
#Mann= 3 , 0 , 0
       0     0.1       0   213.6   0.045       0   228.6     0.1       0
Bank Sta=213.6,228.6
Exp/Cntr=0.3,0.1

Type RM Length L Ch R = 1 ,7876,252.3,228.5,202.8
XS GIS Cut Line= 2
     2040359.912      249023.485     2040025.711      249359.857
#Sta/Elev= 30
       0 1693.35    45.8 1668.45    55.6 1662.38    85.0 1647.15    98.1 1642.00
   111.2 1634.53   114.4 1633.73   127.5 1633.78   134.1 1632.48   137.4 1630.47
   147.2 1620.91   160.2 1612.69   181.7 1609.37   196.7 1609.96   212.6 1609.95
   225.6 1608.92   228.9 1610.44   235.4 1616.78   238.7 1617.62   255.1 1617.95
   278.0 1620.10   300.8 1624.50   317.2 1629.22   330.3 1630.70   343.4 1634.04
   372.8 1639.46   392.4 1642.01   428.4 1650.60   448.0 1653.04   474.2 1659.13
#Mann= 3 , 0 , 0
       0     0.1       0   181.7   0.045       0   196.7     0.1       0
Bank Sta=181.7,196.7
Exp/Cntr=0.3,0.1

Type RM Length L Ch R = 1 ,7647.6,59.2,58.7,59.9
XS GIS Cut Line= 4
     2040022.456      248833.598     2040025.711      248910.638
     2040055.008      249156.949     2040009.435      249261.115
#Sta/Elev= 30
       0 1620.18    32.1 1620.66    48.2 1619.38    67.5 1619.13    90.2 1620.16
   116.3 1620.37   126.1 1618.66   139.1 1613.86   148.9 1611.45   165.2 1611.27
   171.8 1609.66   178.3 1606.93   181.6 1606.33   188.8 1606.09   203.8 1605.49
   210.9 1605.43   217.4 1606.41   227.2 1609.90   240.3 1613.23   279.5 1620.66
   305.6 1627.87   318.6 1629.82   328.4 1630.29   357.6 1633.54   380.4 1636.96
   390.1 1640.00   399.9 1641.76   406.4 1644.26   416.1 1646.51   438.9 1650.42
#Mann= 3 , 0 , 0
       0     0.1       0   188.8   0.045       0   203.8     0.1       0
Bank Sta=188.8,203.8
Exp/Cntr=0.3,0.1

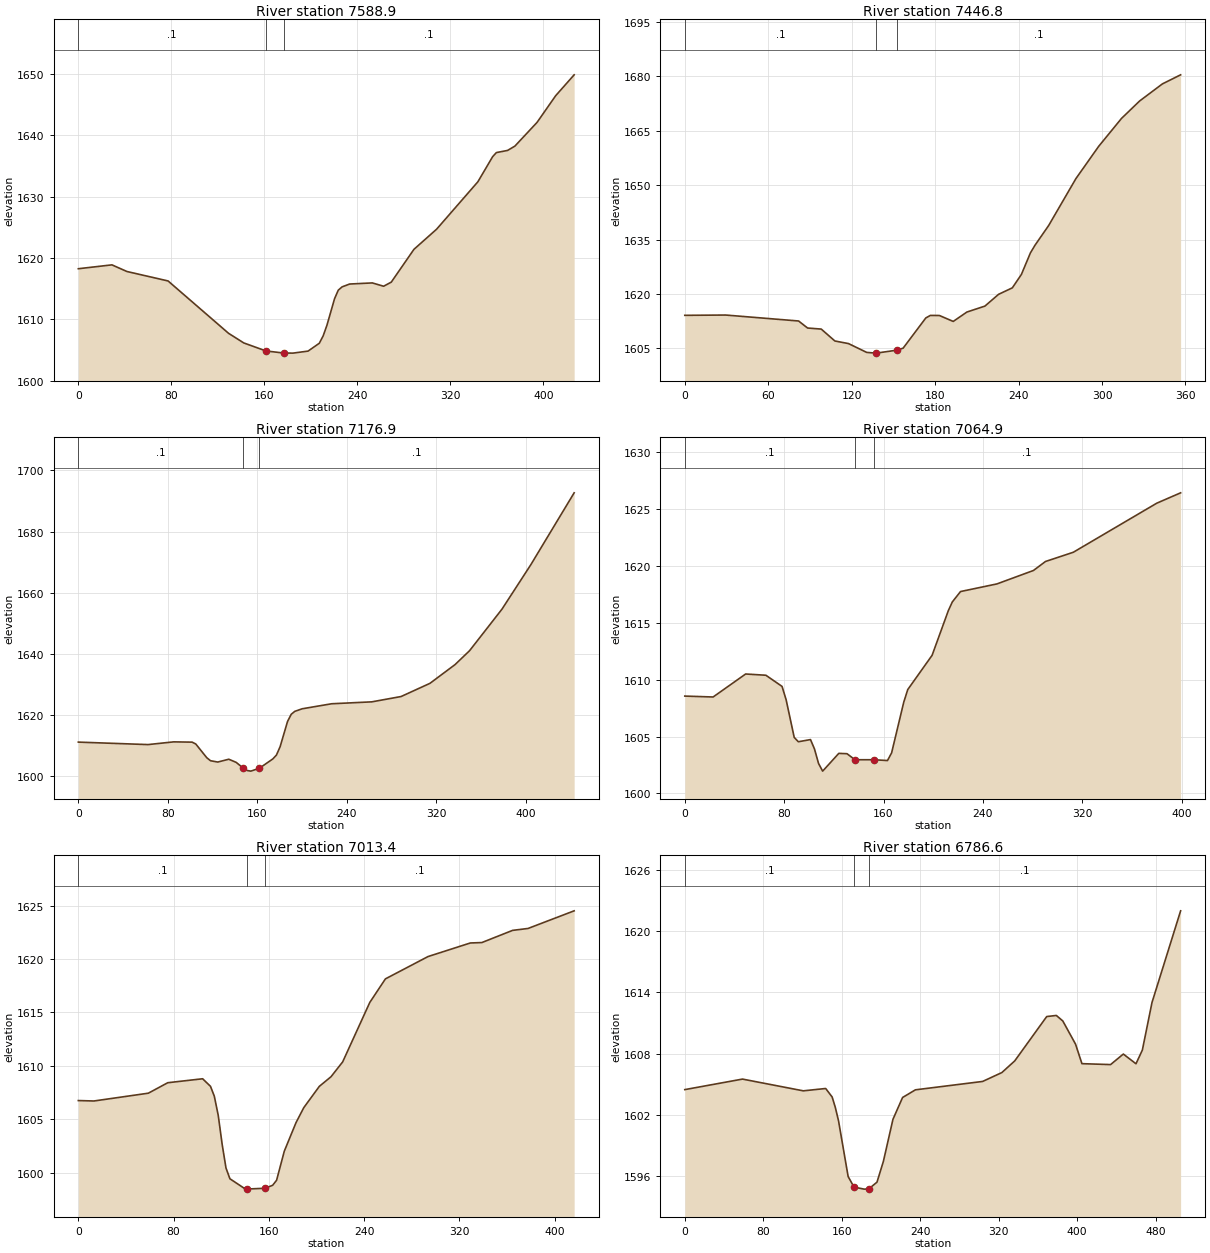
Type RM Length L Ch R = 1 ,7588.9,121.4,142.1,162.8
XS GIS Cut Line= 4
     2039980.138      248827.088     2039979.025      248897.762
     2040012.690      249155.864     2039977.968      249244.839
#Sta/Elev= 30
       0 1618.25    28.9 1618.88    41.8 1617.80    77.2 1616.26   129.2 1607.74
   142.3 1606.17   161.5 1604.86   176.5 1604.53   184.6 1604.51   197.6 1604.84
   207.3 1606.12   210.6 1607.32   213.8 1609.02   220.4 1613.37   223.6 1614.76
   226.9 1615.30   233.4 1615.76   252.9 1615.94   262.6 1615.40   269.2 1616.07
   288.7 1621.41   308.2 1624.69   343.7 1632.41   356.4 1636.50   359.6 1637.16
   369.2 1637.51   375.5 1638.21   394.6 1642.08   410.6 1646.42   426.5 1649.82
#Mann= 3 , 0 , 0
       0     0.1       0   161.5   0.045       0   176.5     0.1       0
Bank Sta=161.5,176.5
Exp/Cntr=0.3,0.1

Type RM Length L Ch R = 1 ,7446.8,243.1,269.9,295.4
XS GIS Cut Line= 2
     2039961.692      248792.365     2039755.528      249083.164
#Sta/Elev= 30
       0 1614.12    29.4 1614.20    81.8 1612.56    88.3 1610.62    98.1 1610.33
   107.9 1607.05   117.7 1606.33   130.8 1603.90   137.4 1603.70   137.8 1603.71
   152.8 1604.53   157.0 1605.08   173.3 1613.40   176.6 1614.10   183.1 1614.07
   193.0 1612.44   202.8 1615.02   215.8 1616.67   225.6 1619.91   235.5 1621.70
   242.0 1625.38   248.5 1631.33   251.8 1633.45   261.6 1638.87   281.2 1651.81
   297.6 1660.72   314.0 1668.41   327.0 1673.21   343.4 1677.93   356.5 1680.43
#Mann= 3 , 0 , 0
       0     0.1       0   137.8   0.045       0   152.8     0.1       0
Bank Sta=137.8,152.8
Exp/Cntr=0.3,0.1

Type RM Length L Ch R = 1 ,7176.9,101,112,123.2
XS GIS Cut Line= 3
     2039917.204      248712.070     2039642.681      248663.242
     2039500.537      248745.707
#Sta/Elev= 30
       0 1611.14    62.3 1610.33    85.3 1611.22   101.7 1611.13   105.0 1610.52
   114.8 1606.04   118.1 1605.06   124.6 1604.62   134.5 1605.54   141.1 1604.51
   146.9 1602.78   150.9 1601.85   154.2 1601.65   161.9 1602.61   173.9 1605.65
   177.1 1606.92   180.4 1609.67   187.0 1617.88   190.3 1620.24   193.5 1621.20
   200.1 1622.04   226.4 1623.68   262.4 1624.31   288.5 1626.05   314.3 1630.36
   336.8 1636.51   349.7 1641.03   378.7 1654.63   404.5 1669.18   443.2 1692.67
#Mann= 3 , 0 , 0
       0     0.1       0   146.9   0.045       0   161.9     0.1       0
Bank Sta=146.9,161.9
Exp/Cntr=0.3,0.1

Type RM Length L Ch R = 1 ,7064.9,51.9,51.5,51.5
XS GIS Cut Line= 3
     2039884.652      248664.327     2039660.042      248485.291
     2039550.450      248462.504
#Sta/Elev= 30
       0 1608.55    22.8 1608.47    49.0 1610.49    65.3 1610.38    78.3 1609.40
    81.6 1608.22    88.1 1604.92    91.4 1604.54   101.2 1604.73   104.4 1603.91
   107.7 1602.63   111.0 1601.96   124.0 1603.52   130.6 1603.49     137 1602.96
     152 1602.96   163.2 1602.89   166.5 1603.56   176.3 1608.02   179.5 1609.12
   199.1 1612.13   212.2 1616.06   215.4 1616.82   222.0 1617.73   251.3 1618.40
   280.7 1619.58   290.4 1620.37   312.8 1621.18   380.0 1625.49   399.2 1626.40
#Mann= 3 , 0 , 0
       0     0.1       0     137   0.045       0     152     0.1       0
Bank Sta=137,152
Exp/Cntr=0.3,0.1

Type RM Length L Ch R = 1 ,7013.4,231.2,226.8,222.3
XS GIS Cut Line= 3
     2039910.693      248620.925     2039686.084      248441.888
     2039559.131      248418.017
#Sta/Elev= 30
       0 1606.75    13.1 1606.71    58.8 1607.44    75.1 1608.42   104.4 1608.79
   111.0 1608.08   114.2 1607.16   117.5 1605.36   120.8 1602.64   124.0 1600.44
   127.3 1599.43   140.4 1598.46   141.8 1598.47   156.8 1598.54   163.2 1598.82
   166.5 1599.29   173.0 1602.02   182.8 1604.68   189.3 1606.08   202.4 1608.08
   212.2 1608.98   222.0 1610.37   244.8 1615.94   257.9 1618.14   293.7 1620.23
   329.2 1621.50   338.9 1621.54   364.7 1622.68   377.7 1622.86   416.4 1624.51
#Mann= 3 , 0 , 0
       0     0.1       0   141.8   0.045       0   156.8     0.1       0
Bank Sta=141.8,156.8
Exp/Cntr=0.3,0.1

Type RM Length L Ch R = 1 ,6786.6,270.2,274.5,278.7
XS GIS Cut Line= 3
     2040040.902      248401.740     2039690.424      248219.449
     2039620.980      248133.728
#Sta/Elev= 30
       0 1604.49    58.8 1605.52   120.8 1604.37   143.6 1604.60   150.2 1603.77
   153.4 1602.76   156.7 1601.44   166.5 1595.98   172.5 1594.95   182.8 1594.75
   187.5 1594.77   195.9 1595.43   202.4 1597.46   212.2 1601.59   222.0 1603.72
   235.1 1604.47   303.6 1605.29   323.2 1606.16   336.3 1607.30   368.9 1611.64
   378.7 1611.75   385.3 1611.21   398.3 1608.94   404.8 1607.03   434.0 1606.94
   447.0 1607.97   459.9 1607.02   466.4 1608.36   476.2 1613.01   505.4 1621.99
#Mann= 3 , 0 , 0
       0     0.1       0   172.5   0.045       0   187.5     0.1       0
Bank Sta=172.5,187.5
Exp/Cntr=0.3,0.1

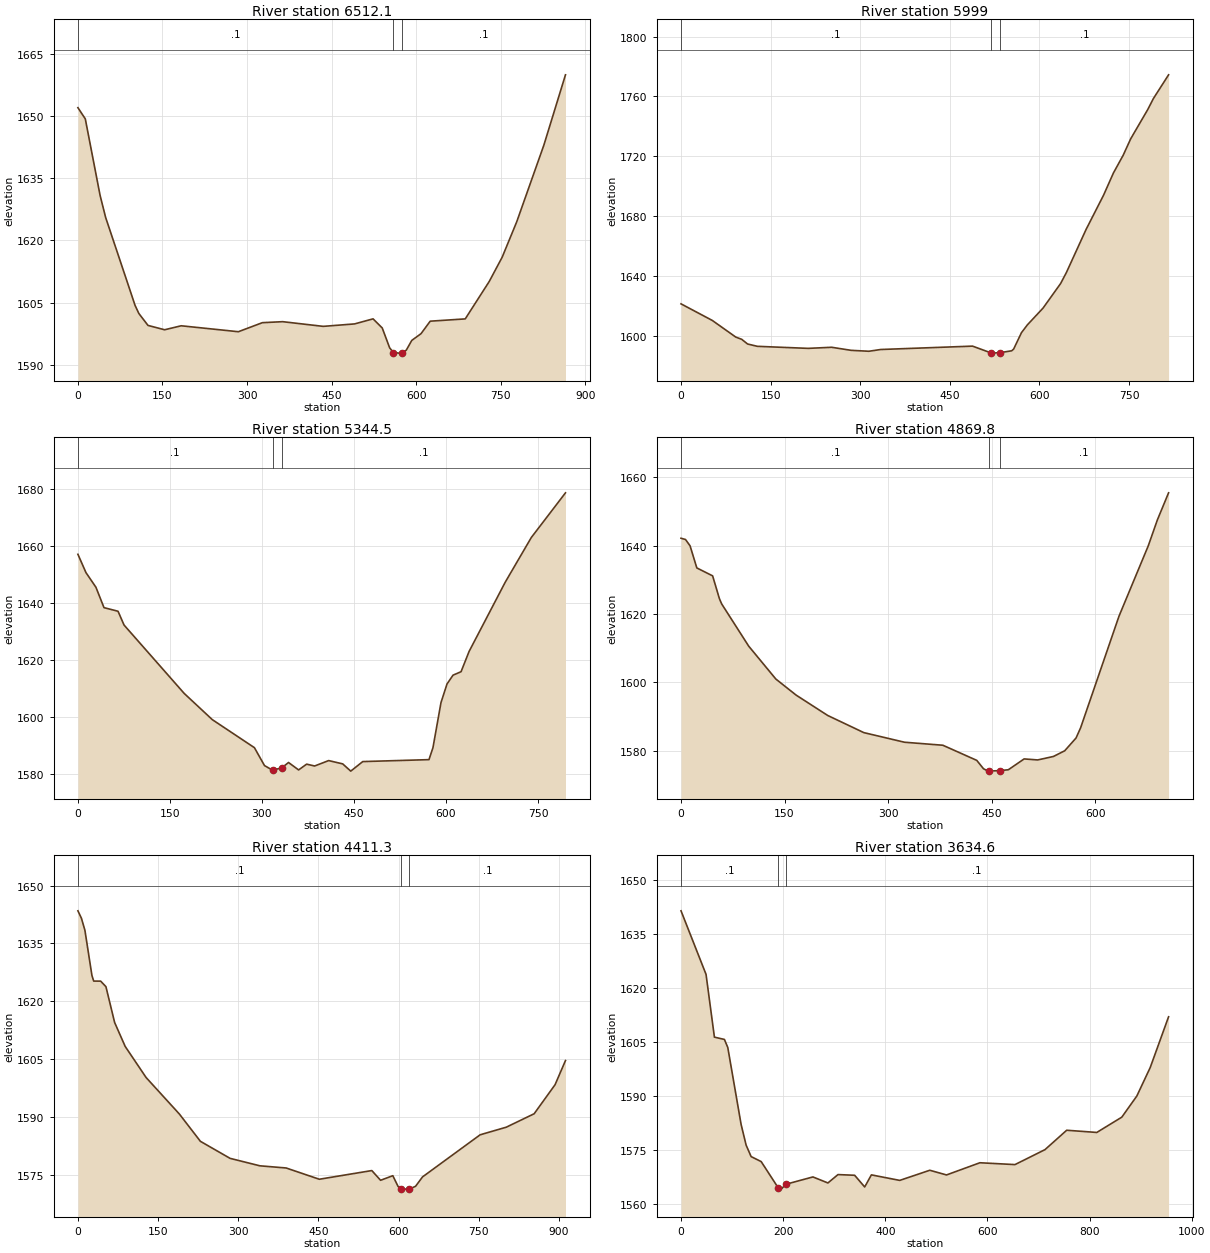
Type RM Length L Ch R = 1 ,6512.1,514.9,513.1,511.4
XS GIS Cut Line= 3
     2040474.828      248439.718     2039873.801      247965.543
     2039825.407      247878.954
#Sta/Elev= 30
       0 1652.00    13.1 1649.30    39.3 1630.88    49.1 1625.57   101.4 1604.34
   108.0 1602.41   124.3 1599.52   153.8 1598.47   183.2 1599.43   284.6 1598.00
   327.2 1600.18   363.2 1600.42   435.1 1599.29   490.7 1599.88   523.5 1601.10
   539.8 1598.90   552.9 1594.12   559.6 1592.99   569.3 1592.84   574.6 1592.90
   582.4 1593.55   592.2 1595.91   608.5 1597.52   624.9 1600.54   687.0 1601.09
   729.6 1610.12   752.5 1615.96   778.4 1624.52   826.4 1642.95   864.8 1659.92
#Mann= 3 , 0 , 0
       0     0.1       0   559.6   0.045       0   574.6     0.1       0
Bank Sta=559.6,574.6
Exp/Cntr=0.3,0.1

Type RM Length L Ch R = 1 ,5999,653.7,654.4,655.9
XS GIS Cut Line= 3
     2040792.421      248078.607     2040226.449      247606.385
     2040163.949      247557.773
#Sta/Elev= 30
       0 1621.30    52.4 1610.20    91.7 1599.07   101.6 1597.59   111.4 1594.46
   127.8 1592.90   212.9 1591.53   252.2 1592.26   285.0 1590.21   314.5 1589.60
   334.2 1590.77   488.1 1593.03   519.6 1588.41   520.9 1588.35   534.6 1588.70
   553.6 1589.91   556.9 1591.07   570.0 1602.03   579.8 1607.20   606.1 1618.46
   635.6 1634.92   645.4 1642.41   678.1 1670.99   707.6 1694.10   724.0 1708.86
   740.3 1720.69   752.9 1731.69   781.4 1751.22   790.9 1758.61   816.3 1774.46
#Mann= 3 , 0 , 0
       0     0.1       0   519.6   0.045       0   534.6     0.1       0
Bank Sta=519.6,534.6
Exp/Cntr=0.3,0.1

Type RM Length L Ch R = 1 ,5344.5,477.5,474.7,469.7
XS GIS Cut Line= 3
     2041200.407      247689.718     2040630.962      247306.037
     2040554.574      247229.648
#Sta/Elev= 30
       0 1657.02    13.1 1650.60    29.4 1645.44    42.5 1638.30    65.4 1637.03
    75.2 1632.19   173.3 1608.18   219.1 1598.99   287.7 1589.16   304.1 1582.88
   317.2 1581.27   332.2 1582.06   343.3 1583.96   359.7 1581.35   372.8 1583.38
   385.8 1582.73   408.7 1584.63   431.6 1583.47   444.7 1580.93   464.3 1584.28
   572.2 1584.96   578.7 1589.16   591.8 1604.99   601.6 1611.51   611.4 1614.60
   624.5 1615.82   637.6 1622.93   696.5 1647.23   739.0 1662.91   794.7 1678.59
#Mann= 3 , 0 , 0
       0     0.1       0   317.2   0.045       0   332.2     0.1       0
Bank Sta=317.2,332.2
Exp/Cntr=0.3,0.1

Type RM Length L Ch R = 1 ,4869.8,456.6,458.6,459.7
XS GIS Cut Line= 2
     2041394.851      247234.857     2040749.018      246948.398
#Sta/Elev= 30
       0 1642.17     6.5 1641.80    13.1 1639.96    22.9 1633.49    45.8 1631.17
    55.6 1624.52    58.9 1622.97    98.1 1610.61   137.4 1601.00   166.8 1596.30
   212.6 1590.34   264.9 1585.33   323.8 1582.52   379.4 1581.64   428.5 1577.22
   438.3 1574.77   444.8 1574.07     447 1574.09     462 1574.22   474.3 1574.47
   497.2 1577.64   516.8 1577.34   539.7 1578.36   556.0 1580.02   572.4 1583.75
   579.0 1586.72   634.6 1619.35   677.1 1639.97   690.2 1647.50   706.5 1655.45
#Mann= 3 , 0 , 0
       0     0.1       0     447   0.045       0     462     0.1       0
Bank Sta=447,462
Exp/Cntr=0.3,0.1

Type RM Length L Ch R = 1 ,4411.3,794.6,776.7,755.9
XS GIS Cut Line= 3
     2041636.171      246925.829     2041021.587      246569.926
     2040823.671      246609.857
#Sta/Elev= 30
       0 1643.44     6.6 1641.51    13.1 1638.39    26.2 1626.70    29.5 1625.24
    42.6 1625.22    52.4 1623.79    68.7 1614.50    88.4 1608.31   127.6 1600.24
   189.8 1590.79   229.1 1583.72   284.7 1579.30   340.4 1577.37   389.5 1576.81
   451.6 1573.89   549.8 1576.14   566.2 1573.62   589.1 1574.81   598.9 1572.04
   604.5 1571.38   618.6 1571.33   619.5 1571.33   631.6 1572.06   644.7 1574.50
   752.5 1585.41   801.4 1587.38   853.5 1590.86   892.6 1598.38   912.1 1604.64
#Mann= 3 , 0 , 0
       0     0.1       0   604.5   0.045       0   619.5     0.1       0
Bank Sta=604.5,619.5
Exp/Cntr=0.3,0.1

Type RM Length L Ch R = 1 ,3634.6,705,704.5,701.5
XS GIS Cut Line= 2
     2041705.615      245976.176     2040802.837      246286.940
#Sta/Elev= 30
       0 1641.33    49.0 1623.72    65.4 1606.32    85.0 1605.68    91.6 1603.44
   117.7 1582.11   127.5 1576.38   137.3 1573.21   157.0 1571.82   190.2 1564.58
   196.2 1564.19   205.2 1565.53   258.3 1567.57   287.7 1565.90   307.4 1568.22
   340.0 1568.03   359.7 1564.79   372.8 1568.14   428.3 1566.61   487.2 1569.42
   519.9 1568.12   585.3 1571.50   654.0 1570.99   712.8 1575.14   755.3 1580.51
   814.2 1579.90   863.2 1584.14   892.6 1589.99   918.8 1597.88   954.8 1611.96
#Mann= 3 , 0 , 0
       0     0.1       0   190.2   0.045       0   205.2     0.1       0
Bank Sta=190.2,205.2
Exp/Cntr=0.3,0.1