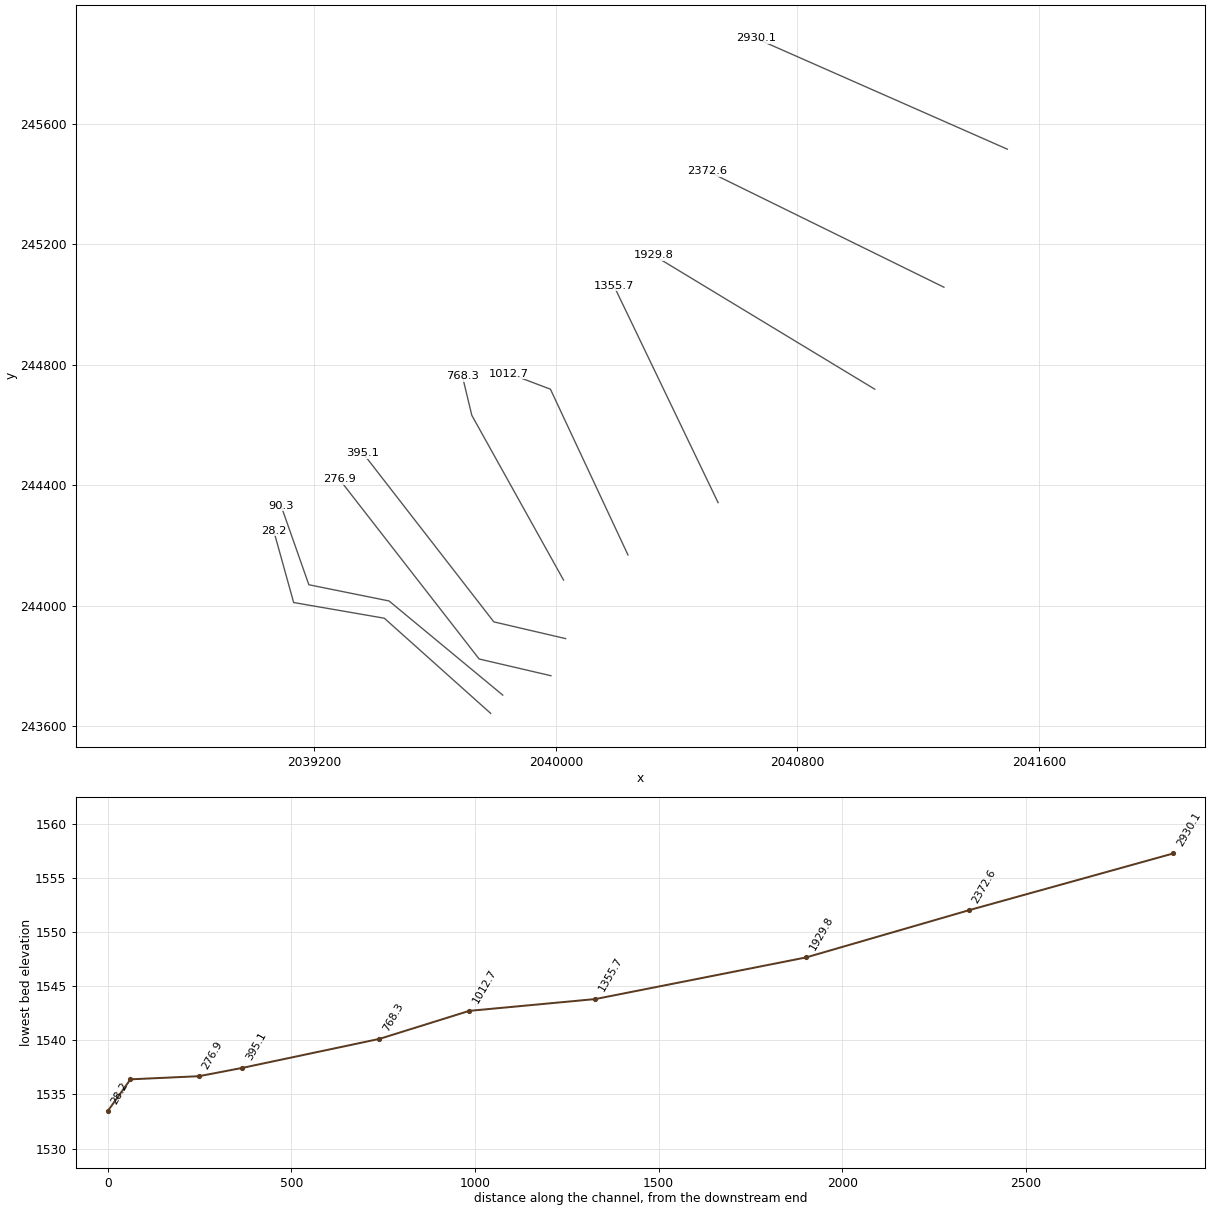
HEC-RAS study HNGRDCK.prj: HNGRDCK

--- HNGRDCK.g01 (geometry) --- (continued)

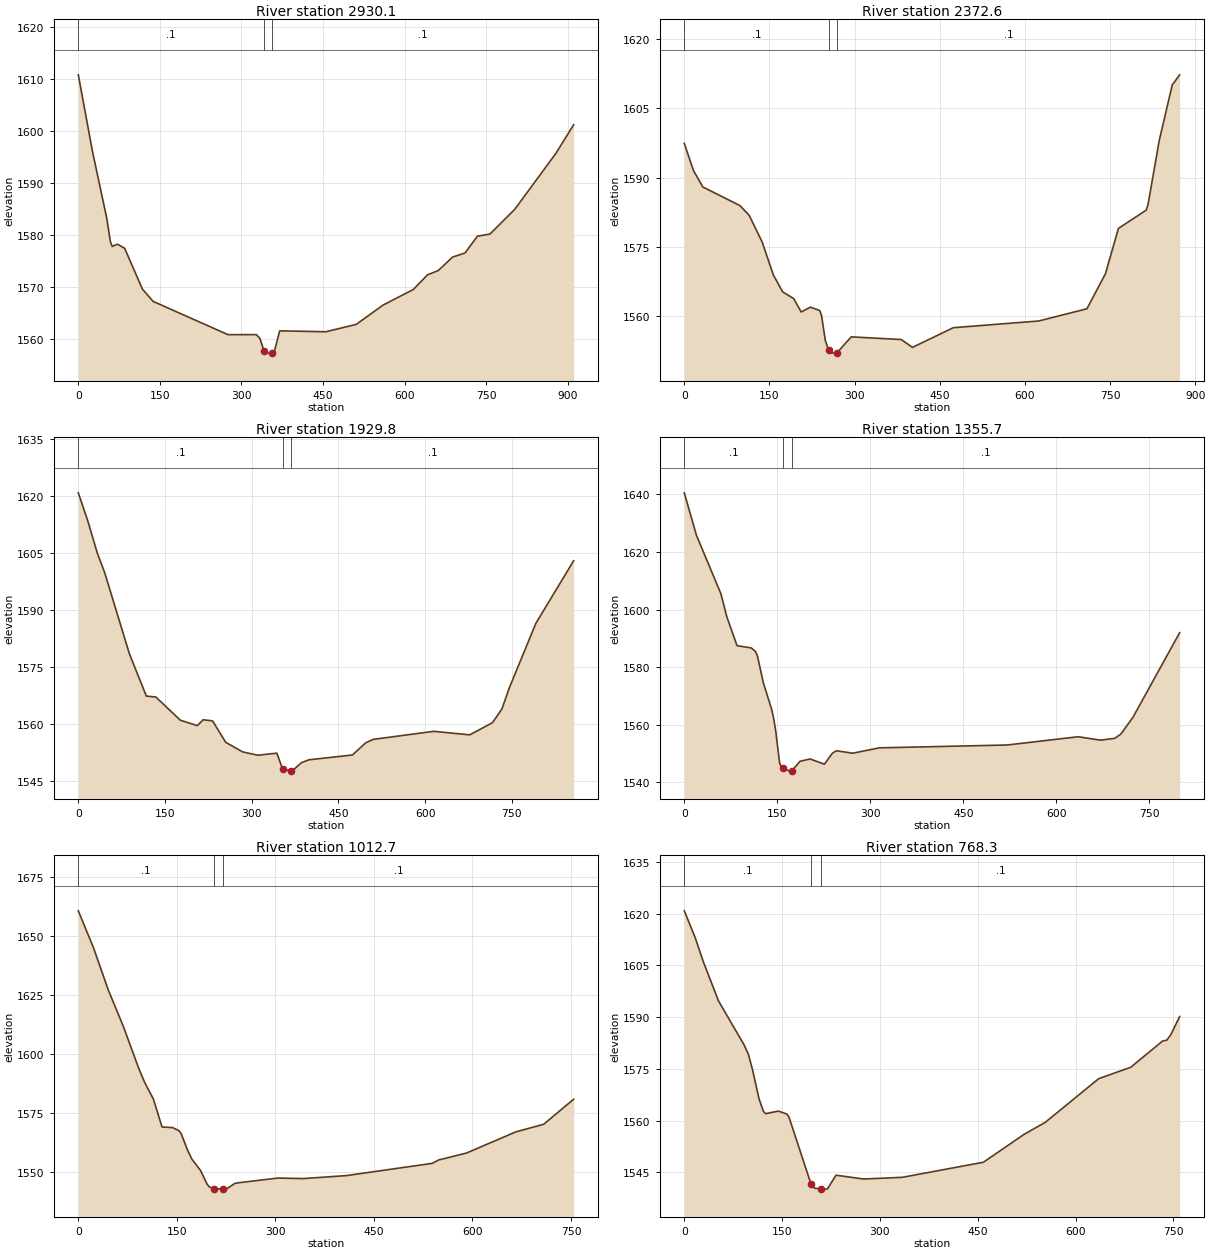
Type RM Length L Ch R = 1 ,2930.1,557.3,557.5,555.3
XS GIS Cut Line= 2
     2041495.546      245516.107     2040662.212      245884.162
#Sta/Elev= 30
       0 1610.78    26.2 1595.98    52.4 1583.18    59.0 1578.71    62.3 1577.80
    72.1 1578.23    85.2 1577.44   118.0 1569.58   137.6 1567.23   275.3 1560.84
   327.7 1560.85   334.2 1560.07   341.3 1557.79   347.4 1557.29   356.3 1557.31
   360.5 1557.56   370.3 1561.57   455.5 1561.40   511.2 1562.82   560.4 1566.52
   616.1 1569.52   642.3 1572.35   661.9 1573.15   688.2 1575.75   711.1 1576.53
   734.0 1579.77   757.0 1580.17   802.8 1584.95   878.2 1595.67   911.0 1601.19
#Mann= 3 , 0 , 0
       0     0.1       0   341.3   0.045       0   356.3     0.1       0
Bank Sta=341.3,356.3
Exp/Cntr=0.3,0.1

Type RM Length L Ch R = 1 ,2372.6,443.2,442.9,441.1
XS GIS Cut Line= 2
     2041285.476      245057.773     2040502.490      245443.190
#Sta/Elev= 30
       0 1597.40    16.3 1591.50    32.7 1587.97    98.1 1583.94   114.4 1581.83
   137.3 1576.04   156.9 1568.94   173.2 1565.30   192.8 1563.82   205.9 1560.94
   222.3 1561.97   238.6 1561.25   241.9 1560.13   248.4 1554.80   254.3 1552.61
   261.5 1552.03   269.3 1552.14   294.2 1555.55   382.4 1554.97   402.0 1553.27
   473.9 1557.53   624.3 1558.98   709.3 1561.62   742.0 1569.20   764.8 1579.00
   813.9 1582.97   817.1 1584.26   836.8 1598.05   859.6 1610.02   872.7 1612.23
#Mann= 3 , 0 , 0
       0     0.1       0   254.3   0.045       0   269.3     0.1       0
Bank Sta=254.3,269.3
Exp/Cntr=0.3,0.1

Type RM Length L Ch R = 1 ,1929.8,587.3,574.1,558.5
XS GIS Cut Line= 2
     2041056.310      244719.232     2040323.671      245163.676
#Sta/Elev= 30
       0 1620.81    16.4 1613.45    32.7 1605.05    45.8 1599.75    88.3 1578.54
   117.7 1567.39   134.1 1567.15   176.6 1561.04   206.0 1559.63   215.9 1561.17
   232.2 1560.88   255.1 1555.22   284.6 1552.71   310.7 1551.85   343.4 1552.39
   353.3 1548.27   368.3 1547.68   369.6 1547.67   385.9 1549.88   399.0 1550.65
   474.2 1551.91   497.1 1555.11   510.2 1556.02   614.9 1558.13   677.0 1557.20
   716.3 1560.38   732.6 1563.96   745.7 1569.61   791.5 1586.51   856.9 1602.97
#Mann= 3 , 0 , 0
       0     0.1       0   353.3   0.045       0   368.3     0.1       0
Bank Sta=353.3,368.3
Exp/Cntr=0.3,0.1

Type RM Length L Ch R = 1 ,1355.7,343.3,342.9,342.8
XS GIS Cut Line= 2
     2040537.212      244342.496     2040191.726      245062.982
#Sta/Elev= 30
       0 1640.56    19.6 1625.81    59.0 1605.53    68.8 1597.36    85.1 1587.44
   108.1 1586.64   114.6 1585.47   117.9 1583.93   127.7 1574.41   140.8 1565.37
   144.1 1562.25   147.4 1557.89   153.9 1546.44   158.5 1544.85   170.3 1543.82
   173.5 1543.94   186.7 1547.25   203.0 1548.04   226.0 1546.24   239.1 1550.11
   245.6 1550.89   271.8 1550.05   314.4 1551.91   520.7 1552.90   635.3 1555.77
   671.3 1554.58   694.2 1555.22   704.1 1556.68   723.7 1562.53   799.0 1591.94
#Mann= 3 , 0 , 0
       0     0.1       0   158.5   0.045       0   173.5     0.1       0
Bank Sta=158.5,173.5
Exp/Cntr=0.3,0.1

Type RM Length L Ch R = 1 ,1012.7,242.5,244.5,247
XS GIS Cut Line= 3
     2040238.601      244168.885     2039981.657      244719.232
     2039844.504      244771.315
#Sta/Elev= 30
       0 1660.54    22.9 1645.07    45.7 1626.97    68.6 1611.60    91.4 1594.28
   101.2 1587.77   114.3 1580.87   127.4 1569.04   143.7 1568.78   153.5 1567.42
   156.7 1566.13   166.5 1559.10   173.1 1555.31   186.1 1550.63   195.9 1544.90
   199.2 1543.71     206 1542.93     221 1542.81   225.3 1542.73   238.4 1545.16
   244.9 1545.46   303.7 1547.41   342.9 1547.20   408.2 1548.46   538.8 1553.64
   548.6 1555.07   591.0 1558.01   666.1 1566.97   708.4 1570.18   754.1 1580.80
#Mann= 3 , 0 , 0
       0     0.1       0     206   0.045       0     221     0.1       0
Bank Sta=206,221
Exp/Cntr=0.3,0.1

Type RM Length L Ch R = 1 ,768.3,368.8,373.1,375.1
XS GIS Cut Line= 3
     2040025.060      244085.551     2039721.240      244632.426
     2039689.990      244762.635
#Sta/Elev= 30
       0 1620.83    16.4 1613.22    29.5 1605.91    52.4 1594.74    91.7 1581.96
    98.3 1579.25   104.8 1574.64   114.6 1566.34   121.2 1562.73   124.5 1562.02
   144.1 1562.76   157.2 1561.93   160.5 1561.03   194.4 1541.56   199.8 1540.41
   209.4 1540.23   216.2 1540.14   219.4 1540.19   232.6 1544.18   275.1 1543.07
   334.1 1543.56   458.6 1547.93   520.8 1556.00   553.5 1559.51   635.4 1572.17
   684.4 1575.46   733.4 1583.08   739.9 1583.34   746.4 1585.06   759.5 1590.20
#Mann= 3 , 0 , 0
       0     0.1       0   194.4   0.045       0   209.4     0.1       0
Bank Sta=194.4,209.4
Exp/Cntr=0.3,0.1

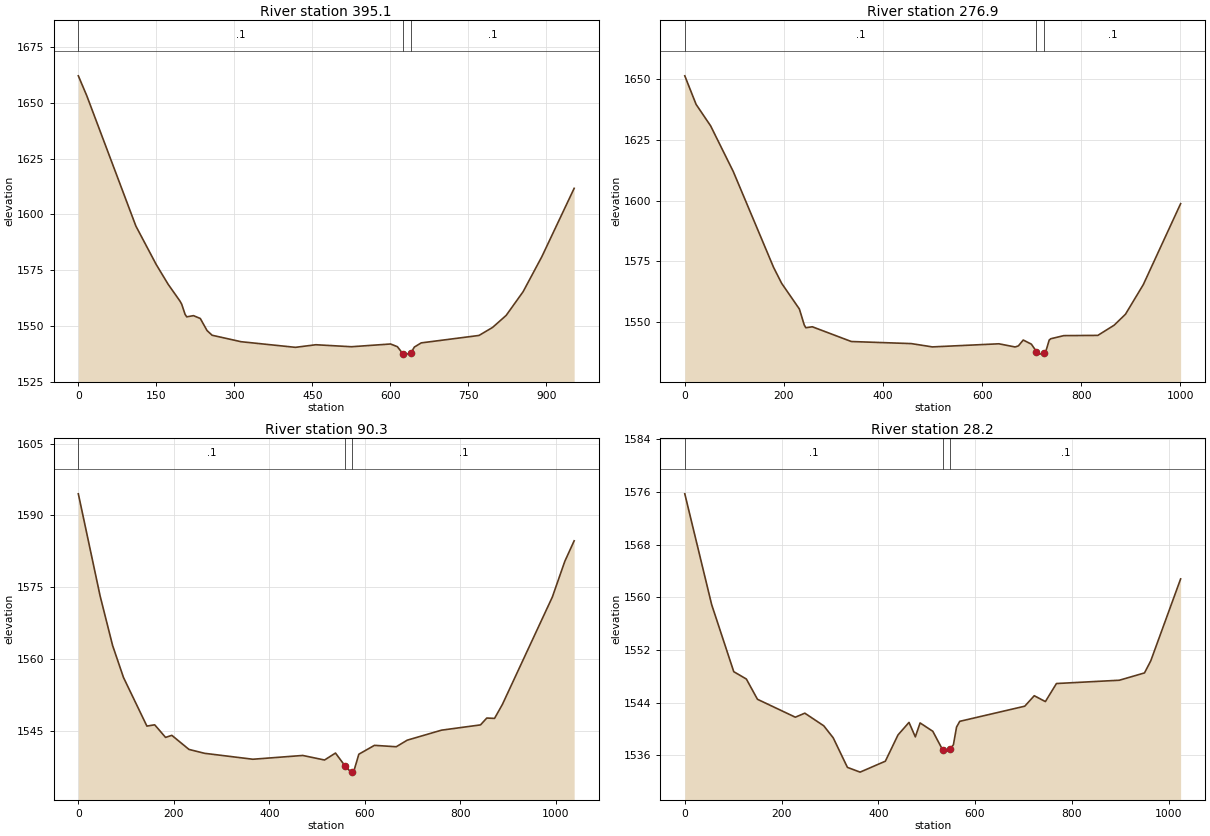
Type RM Length L Ch R = 1 ,395.1,118.5,118.2,117.8
XS GIS Cut Line= 3
     2040032.004      243891.107     2039794.157      243946.662
     2039360.129      244507.426
#Sta/Elev= 30
       0 1662.06    16.3 1653.12   110.7 1594.78   149.8 1577.57   172.6 1568.77
   195.4 1561.23   198.7 1559.85   205.2 1555.31   208.4 1554.15   221.4 1554.69
   234.5 1553.42   247.5 1548.01   257.3 1545.91   312.9 1543.02   417.4 1540.50
   456.7 1541.66   525.3 1540.77   600.4 1542.00   613.5 1540.79   623.9 1537.68
   629.8 1537.46   638.9 1537.80   646.2 1540.64   659.3 1542.49   770.4 1545.82
   796.5 1549.41   822.6 1554.78   855.3 1565.43   891.3 1581.11   953.4 1611.69
#Mann= 3 , 0 , 0
       0     0.1       0   623.9   0.045       0   638.9     0.1       0
Bank Sta=623.9,638.9
Exp/Cntr=0.3,0.1

Type RM Length L Ch R = 1 ,276.9,170.4,186.7,202.6
XS GIS Cut Line= 3
     2039983.393      243767.843     2039745.546      243823.398
     2039282.004      244420.621
#Sta/Elev= 30
       0 1651.47    22.8 1639.70    52.1 1630.83    97.7 1612.04   179.1 1572.48
   195.4 1565.89   231.2 1555.29   241.0 1548.70   244.2 1547.58   257.3 1547.97
   335.9 1541.89   457.0 1541.03   499.5 1539.67   633.7 1540.95   666.4 1539.64
   673.0 1540.09   682.8 1542.50   699.2 1540.80   709.5 1537.74   715.5 1536.69
   724.5 1536.99   728.6 1538.00   735.2 1542.50   738.4 1543.03   764.6 1544.32
   833.3 1544.42   866.1 1548.61   889.0 1553.13   925.0 1565.36  1000.3 1598.74
#Mann= 3 , 0 , 0
       0     0.1       0   709.5   0.045       0   724.5     0.1       0
Bank Sta=709.5,724.5
Exp/Cntr=0.3,0.1

Type RM Length L Ch R = 1 ,90.3,61.4,62.1,62.7
XS GIS Cut Line= 4
     2039823.671      243703.607     2039446.935      244016.107
     2039181.310      244069.926     2039089.296      244332.079
#Sta/Elev= 30
       0 1594.50    45.7 1573.14    71.8 1562.83    94.6 1556.15   143.6 1546.01
   159.9 1546.28   182.7 1543.65   195.8 1544.08   231.7 1541.14   264.3 1540.33
   365.5 1539.09   469.9 1539.88   515.6 1538.93   538.5 1540.38   558.8 1537.66
   571.1 1536.40   573.8 1536.42   577.6 1536.82   587.4 1540.14   620.1 1541.99
   665.8 1541.70   688.7 1543.07   760.5 1545.16   842.2 1546.26   855.3 1547.69
   871.6 1547.62   888.0 1550.53   992.6 1572.95  1018.7 1580.40  1038.3 1584.69
#Mann= 3 , 0 , 0
       0     0.1       0   558.8   0.045       0   573.8     0.1       0
Bank Sta=558.8,573.8
Exp/Cntr=0.3,0.1

Type RM Length L Ch R = 1 ,28.2,25,28.2,31.4
XS GIS Cut Line= 4
     2039783.740      243642.843     2039431.310      243958.815
     2039130.962      244010.898     2039064.990      244248.746
#Sta/Elev= 30
       0 1575.70    55.5 1558.89   101.2 1548.70   127.3 1547.58   150.2 1544.51
   228.5 1541.79   248.1 1542.40   287.3 1540.48   306.8 1538.66   336.2 1534.17
   362.4 1533.45   414.6 1535.11   440.7 1539.09   463.5 1541.00   476.6 1538.80
   486.4 1540.92   512.7 1539.65   533.6 1536.75   548.6 1536.95   555.3 1537.61
   561.8 1540.29   568.4 1541.16   702.8 1543.46   722.4 1545.05   745.4 1544.16
   768.3 1546.90   898.3 1547.40   950.3 1548.51   963.3 1550.35  1025.0 1562.78
#Mann= 3 , 0 , 0
       0     0.1       0   533.6   0.045       0   548.6     0.1       0
Bank Sta=533.6,548.6
Exp/Cntr=0.3,0.1